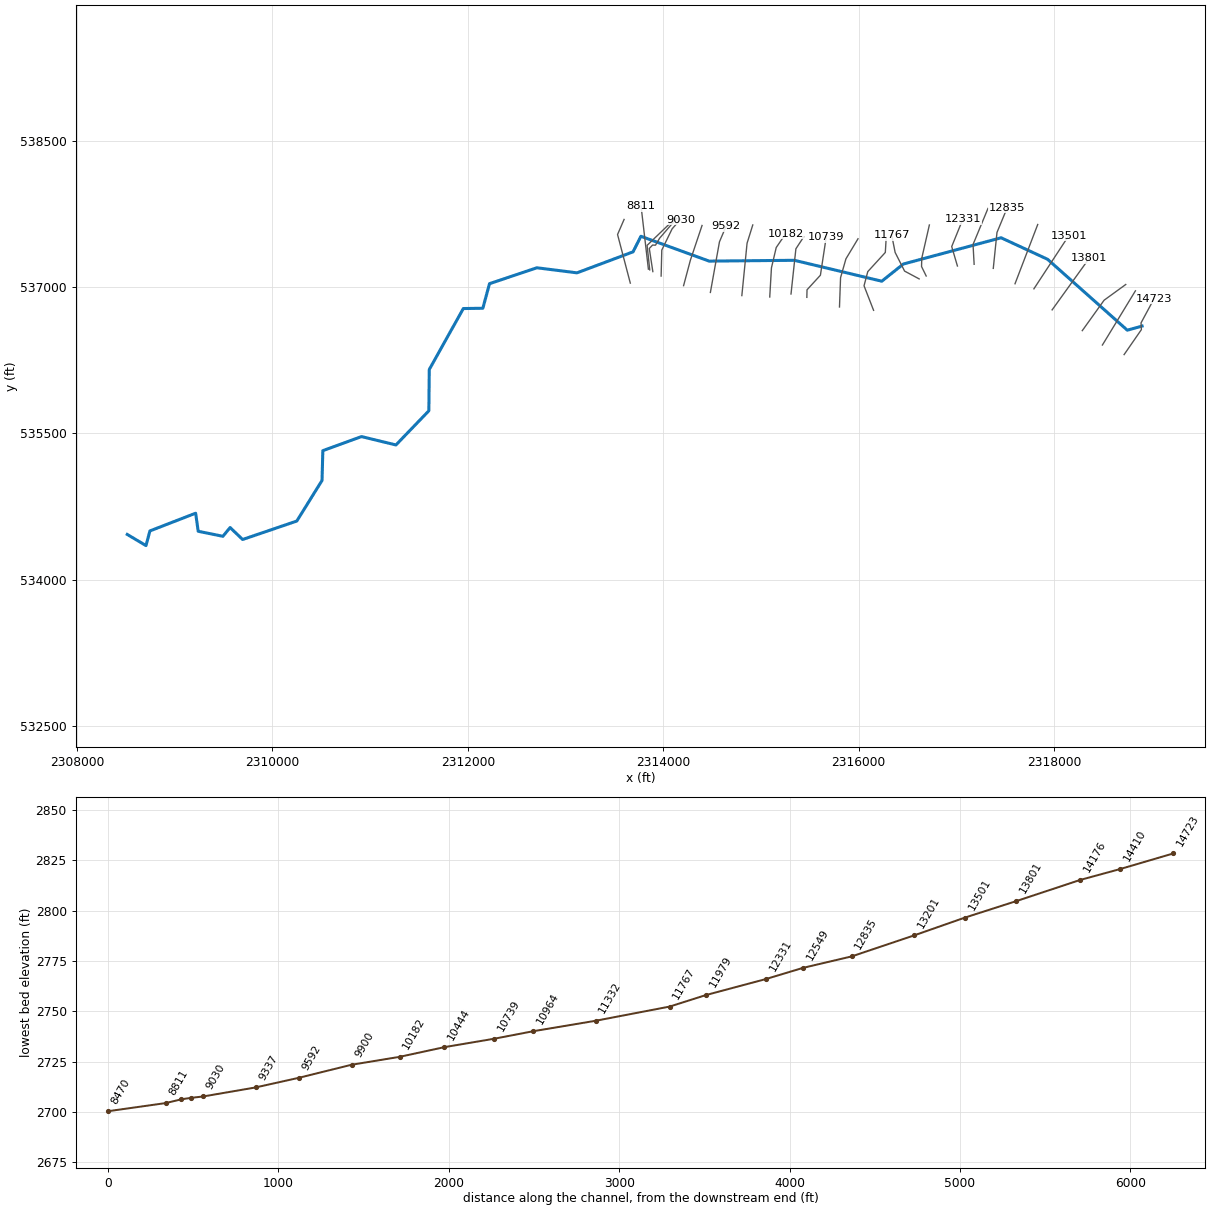
--- BFFLRN.prj (project) ---

Proj Title=BFFLRN
Current Plan=p01
Default Exp/Contr=0,0
English Units
Geom File=g01
Flow File=f01
Plan File=p01
Background Map Layer=Inundation Boundary (01pct Value_0)
BEGIN DESCRIPTION:
----------MODEL BY WOOD PLC 2021----------
Stream Name: Buffalo Run
Flood Zone: Enhanced Approximate
Pocahontas County, WV
HEC-RAS Version: RAS 6.1.0
Vertical Datum: NAVD88
Projection: NAD 1983 StatePlane West Virginia S FIPS 4702 (US Feet)
Terrain: 1-meter LIDAR (FEMA Region III 3DEP collected 2016-2018)
Land Use: 2019 NLCD
Hydrologic Method:
WV SIR2010-5033 regression equations
Model Notes:
Normal depth tie in to Deer Creek
XS 6062 is weirdly oriented to fill the gap in the floodplain
END DESCRIPTION:
DSS Export Rating Curves= 0
DSS Export Rating Curve Sorted= 0
DSS Export Volume Flow Curves= 0
DXF OffsetX= 0
DXF OffsetY= 0
DXF ScaleX= 0
DXF ScaleY= 0

--- BFFLRN.p01 (plan) ---

Plan Title=Floodplain
Program Version=6.10
Short Identifier=Floodplain
Geom File=g01
Flow File=f01
Subcritical Flow
K Sum by GR= 0
Std Step Tol= 0.01
Critical Tol= 0.01
Num of Std Step Trials= 20
Max Error Tol= 0.3
Flow Tol Ratio= 0.001
Split Flow NTrial= 30
Split Flow Tol= 0.02
Split Flow Ratio= 0.02
Log Output Level= 0
Friction Slope Method= 1
Unsteady Friction Slope Method= 2
Unsteady Bridges Friction Slope Method= 1
Parabolic Critical Depth
Global Vel Dist= 0 , 0 , 0
Global Log Level= 0
CheckData=True
Encroach Param=-1 ,0,0, 0
Mapping Interval=1HOUR
Computation Time Step Use Courant=        0
Computation Time Step Use Time Series=    0
Computation Time Step Count To Double=0
Computation Time Step Max Doubling=0
Computation Time Step Max Halving=0
Computation Time Step Residence Courant=0
Run HTab= 0
Run UNet= 0
Run Sediment= 0
Run PostProcess= 0
Run WQNet= 0
Run RASMapper=-1
UNET Theta= 0
UNET Theta Warmup= 0
UNET ZTol= 0
UNET ZSATol= 0
UNET MxIter= 0
UNET Max Iter WO Improvement= 0
UNET MaxInSteps= 0
UNET DtIC= 0
UNET DtMin= 0
UNET MaxCRTS= 0
UNET WFStab= 0
UNET SFStab= 0
UNET WFX= 1
UNET SFX= 1
UNET Gravity=32.174
UNET 1D Methodology=Finite Difference
UNET DSS MLevel= 1
UNET Pardiso=0
UNET DZMax Abort= 0
UNET Use Existing IB Tables= 0
UNET Froude Reduction=False
UNET Froude Limit= 0
UNET Froude Power= 0
UNET D1 Cores= 0
UNET WindReference=Eulerian
UNET WindDragFormulation=Hsu (1988)
UNET D2 Coriolis=0
UNET D2 Cores= 0
UNET D2 Theta= 1
UNET D2 Theta Warmup= 1
UNET D2 Z Tol= 0.01
UNET D2 Volume Tol= 0.01
UNET D2 Max Iterations= 20
UNET D2 Equation= 0
UNET D2 RampUpFraction=0.1
UNET D2 TimeSlices= 1
UNET D2 Turbulence Formulation=Non-Conservative (original)
UNET D2 Eddy Viscosity=0.3
UNET D2 Transverse Eddy Viscosity=0.1
UNET D2 Smagorinsky Mixing=0
UNET D2 BCVolumeCheck=0
UNET D2 Cores=0
UNET D2 SolverType=PARDISO (Direct)
UNET D2 Minimum Iterations= 2147483647
UNET D2 Maximum Iterations= 2147483647
UNET D2 Restart Number= 10
UNET D2 Relaxation Coeff=1.3
UNET D2 SOR Precondition Iterations= 10
UNET D2 ILUT Maximum Fill= 8
UNET D2 ILUT Tolerance=1E-08
UNET D1D2 MaxIter= 0
UNET D1D2 ZTol=0.01
UNET D1D2 QTol=0.1
UNET D1D2 MinQTol=1
Write IC File= 0
Write IC File at Fixed DateTime=0
Write IC File at Sim End=0
Echo Input=False
Echo Parameters=False
Echo Output=False
Write Detailed= 0
HDF Write Warmup=0
HDF Write Time Slices=0
HDF Flush=0
HDF Compression= 1
HDF Chunk Size= 1
HDF Spatial Parts= 1
HDF Use Max Rows=0
HDF Fixed Rows= 1
Calibration Method= 0
Calibration Iterations= 20
Calibration Max Change=0.05
Calibration Tolerance=0.2
Calibration Maximum=1.5
Calibration Minimum=0.5
Calibration Optimization Method= 1
WQ AD Non Conservative
WQ ULTIMATE=-1
WQ Max Comp Step=1HOUR
WQ Output Interval=15MIN
WQ Output Selected Increments= 0
WQ Output face flow=0
WQ Output face velocity=0
WQ Output face area=0
WQ Output face dispersion=0
WQ Output cell volume=0
WQ Output cell surface area=0
WQ Output cell continuity=0
WQ Output cumulative cell continuity=0
WQ Output face conc=0
WQ Output face dconc_dx=0
WQ Output face courant=0
WQ Output face peclet=0
WQ Output face adv mass=0
WQ Output face disp mass=0
WQ Output cell mass=0
WQ Output cell source sink temp=0
WQ Output nsm pathways=0
WQ Output nsm derived pathways=0
WQ Create Restart=0
WQ Fixed Restart=0
WQ System Summary=0
WQ Write To DSS=0
Sorting and Armoring Iterations= 10
XS Update Threshold= 0.02
Bed Roughness Predictor= 0
Hydraulics Update Threshold= 0.02
Energy Slope Method= 1
Volume Change Method= 1
Sediment Retention Method= 0
Sediment TS Multiplier= 1
Warm Up Method= 0
XS Weighting Method= 0
Number of US Weighted Cross Sections= 1
Number of DS Weighted Cross Sections= 1
Upstream XS Weight=0
Main XS Weight=1
Downstream XS Weight=0
Number of DS XS's Weighted with US Boundary= 1
Upstream Boundary Weight= 1
Weight of XSs Associated with US Boundary= 0
Number of US XS's Weighted with DS Boundary= 1
Downstream Boundary Weight= 0.5
Weight of XSs Associated with DS Boundary= 0.5
Percentile Method= 0
Sediment Output Level= 3
Mass or Volume Output= 0
Output Increment Type= 1
Profile and TS Output Increment= 1
Transport Output Increment 1
XS Output Flag= 0
XS Output Increment= 10
Read HDF5 Sediment Hotstart= 0
Sediment Hotstart Type= 0
Write Gradation File= 0
Read Gradation Hotstart= 0
Write HDF5 File= 1
Write Binary Output= 1
Write DSS Sediment File= 0
DSS Sediment Output Type= 1
SV Curve= 0
Specific Gage Flag= 0
Subcell Erosion Methods= 0
Subcell Deposition Methods= 0
Advection Scheme= 1
Matrix Solver= 0
Implicit Weighting Factor= 1
Maximum Outer Loop Convergence Iterations= 5
Convergence Maximum Absolute= 0.001
Convergence RMSE= 0.0001
Grain Fractions Max Abs Error= 0.001
Max Subgrid Regions= 1
Max Subgrid Length Scale= 3.402823E+38
Initial Layer Thickness= 3.402823E+38
Min Layer Thickness= 3.402823E+38
Max Layer Thickness= 3.402823E+38
Number of Layers= 5

--- BFFLRN.f01 (steady flow) ---

Flow Title=Flow
Program Version=6.10
Number of Profiles= 6
Profile Names=01pct,10pct,04pct,02pct,0_2pct,01plus
River Rch & RM=BFFLRN,Main            ,14723
     734     391     518     622    1020    1090
River Rch & RM=BFFLRN,Main            ,11332
     830     445     587     705    1150    1230
River Rch & RM=BFFLRN,Main            ,4812
     924     497     655     785    1280    1370
Boundary for River Rch & Prof#=BFFLRN,Main            , 1
Up Type= 0
Dn Type= 3
Dn Slope=0.00732
Boundary for River Rch & Prof#=BFFLRN,Main            , 2
Up Type= 0
Dn Type= 3
Dn Slope=0.00732
Boundary for River Rch & Prof#=BFFLRN,Main            , 3
Up Type= 0
Dn Type= 3
Dn Slope=0.00732
Boundary for River Rch & Prof#=BFFLRN,Main            , 4
Up Type= 0
Dn Type= 3
Dn Slope=0.00732
Boundary for River Rch & Prof#=BFFLRN,Main            , 5
Up Type= 0
Dn Type= 3
Dn Slope=0.00732
Boundary for River Rch & Prof#=BFFLRN,Main            , 6
Up Type= 0
Dn Type= 3
Dn Slope=0.00732
DSS Import GetInterval= 0
DSS Import GetPeak= 0
DSS Import FillOption= 0

--- BFFLRN.g01 (geometry) ---

Geom Title=Geometry
Program Version=6.10

River Reach=BFFLRN          ,Main
Reach XY= 30
     2318903.162      536599.761 2318751.5341954 536557.44646129
     2317935.647      537283.636      2317459.42      537504.036
     2316458.648537234.977136991     2316238.313      537059.108
     2315342.725      537273.355     2314470.662       537264.96
     2313771.798      537519.252     2313691.936      537360.153
     2313117.585      537144.863     2312707.053      537196.731
2312222.31118405537033.909370247     2312153.953      536782.069
     2311954.009      536779.1812311605.47074554536154.704928607
2311601.34497015535731.822994639     2311264.318      535381.959
     2310911.311      535467.672     2310515.822      535323.234
 2310507.6257591535018.097266282     2310249.367      534602.453
      2309694.84      534413.403     2309566.396        534535.9
     2309492.857      534446.185     2309239.893      534497.709
     2309213.774      534682.788      2308745.61      534501.183
     2308705.292      534351.052     2308513.638      534465.327

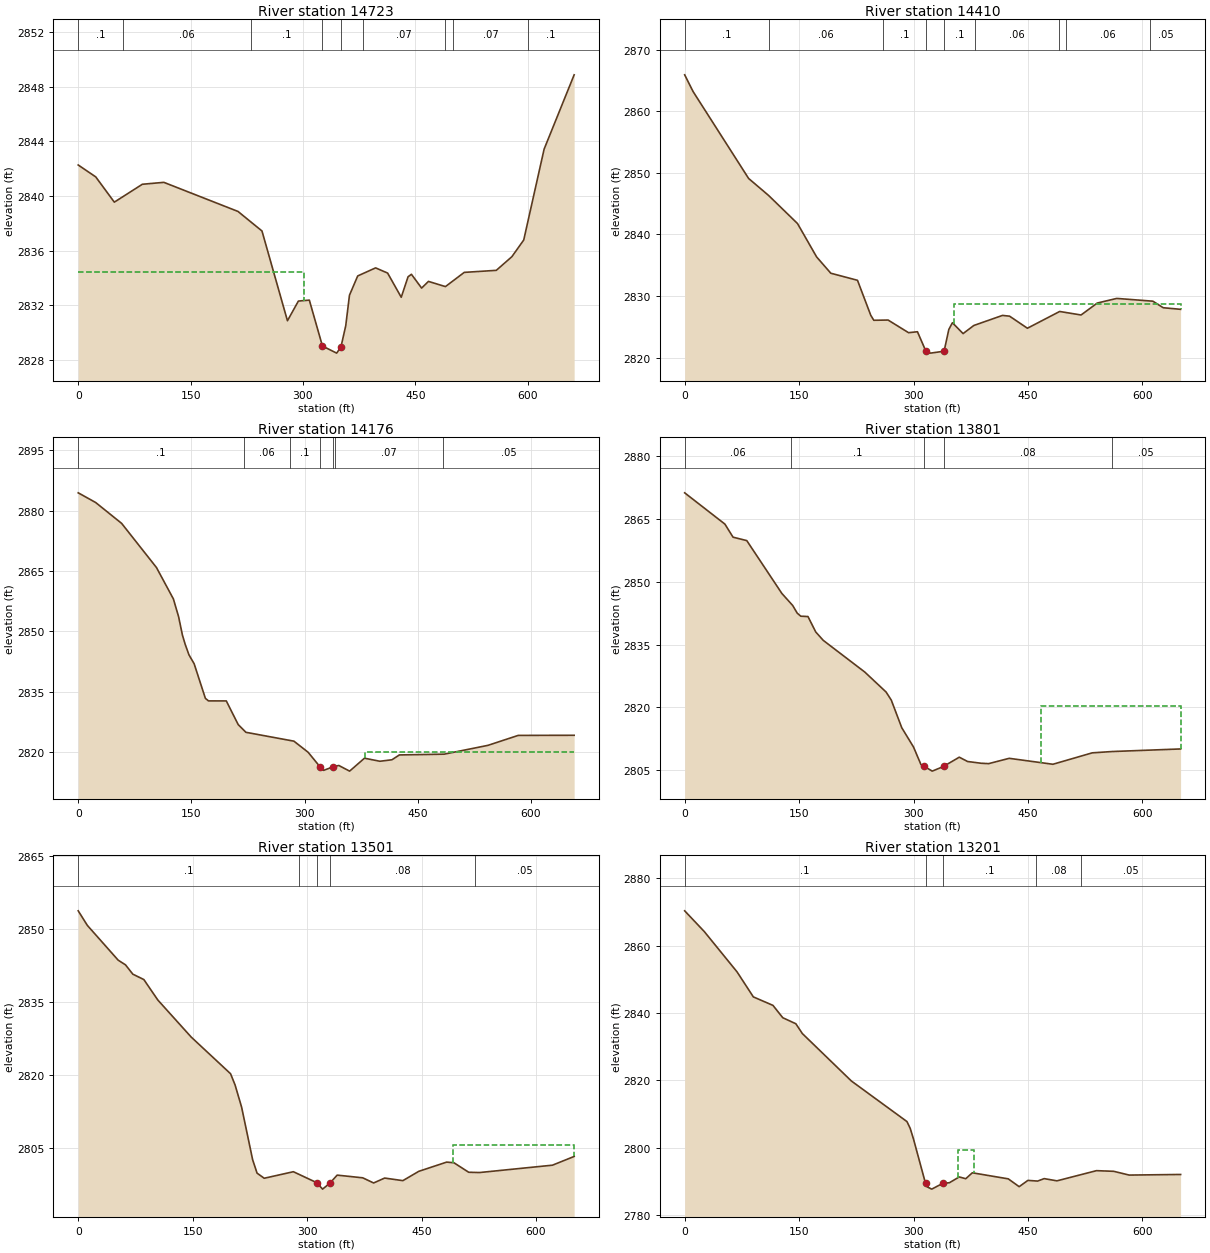
Type RM Length L Ch R = 1 ,14723   ,313,313,313
XS GIS Cut Line= 4
 2318718.8640639536307.4479337982318895.94962597536563.538014118
 2318892.1872396536632.2015652752319025.63106168536880.504657933
#Sta/Elev= 30
       0 2842.28    23.4 2841.41    48.2 2839.56    85.6 2840.87   114.3 2841.01
   213.3 2838.88   245.3 2837.45   279.3 2830.88   293.9 2832.32   308.5 2832.39
     326 2829.03     345 2828.51   350.7 2828.96   357.1 2830.51   362.1 2832.75
   373.1 2834.16     397 2834.75     413 2834.37   431.2  2832.6   440.3  2834.1
   444.8 2834.28   458.4 2833.27   467.5 2833.76   490.2 2833.38   515.3 2834.42
   558.1 2834.57   578.9 2835.57   594.7 2836.79   621.9 2843.44     662 2848.88
#Mann= 9 ,-1,0
       0      .1       0      60     .06       0     230      .1       0
     326    .045       0   350.7      .1       0  380.12     .07       0
  490.12      .1       0  500.12     .07       0  600.12      .1       0
#XS Ineff= 2 , 0
           301.3 2834.47
Permanent Ineff=
       F       F
Bank Sta=326,350.7
XS Rating Curve= 0 ,0
Exp/Cntr(USF)=0,0
Exp/Cntr=0.3,0.1

Type RM Length L Ch R = 1 ,14410   ,235.4,234.3,231.8
XS GIS Cut Line= 2
2318496.64671078 536405.481366092318834.70171797536960.655944138
#Sta/Elev= 30
       0 2865.89    11.1 2863.16    83.8 2849.07     110 2846.31   147.9 2841.75
   172.9 2836.34   191.5 2833.69   226.5 2832.54   243.9 2826.86   247.9 2826.05
   266.6 2826.09   293.4 2824.04   305.1 2824.19   316.22821.013   322.1 2820.72
     340 2821.03   346.2 2824.56   350.9 2825.65   364.9 2823.89     379 2825.21
   416.5 2826.84   425.8 2826.72   449.2 2824.76   491.5 2827.48   519.5 2826.91
   540.8 2828.85   566.3  2829.6   613.6 2829.15   627.2 2828.09     650 2827.83
#Mann= 9 ,-1,0
       0      .1       0     110     .06       0     260      .1       0
   316.2    .045       0     340      .1       0     380     .06       0
     490     .07       0     500     .06       0     610     .05       0
#XS Ineff= 2 , 0
                          352.96         2828.68
Permanent Ineff=
       F       F
Bank Sta=316.2,340
XS Rating Curve= 0 ,0
Exp/Cntr(USF)=0,0
Exp/Cntr=0.3,0.1

Type RM Length L Ch R = 1 ,14176   ,375.2,375.1,374.9
XS GIS Cut Line= 3
2318290.69403019536552.9089424412318514.06740994  536864.5289233
2318735.44617159 537025.40640617
#Sta/Elev= 30
       0 2884.41    23.1 2882.01    57.5 2876.83   103.7 2865.86   126.1 2858.07
     133 2853.66   138.1 2849.07   141.7 2846.82   146.7  2844.2   153.6 2841.97
   168.5 2833.38   172.6 2832.75   196.2 2832.74     212 2826.86   222.2 2824.95
   285.8 2822.75   304.6    2820320.99282816.242   325.2  2815.5338.19242816.418
   345.3 2816.71   359.6 2815.31   379.3 2818.52   399.7 2817.76   415.7 2818.13
   425.5 2819.33   484.9 2819.52   542.9 2821.71     583 2824.18   657.1 2824.21
#Mann= 7 ,-1,0
       0      .1       0     220     .06       0     280      .1       0
320.9928    .045       0338.1924      .1       0     340     .07       0
  483.41     .05       0
#XS Ineff= 2 , 0
                          379.67          2820.1
Permanent Ineff=
       F       F
Bank Sta=320.9928,338.1924
XS Rating Curve= 0 ,0
Exp/Cntr(USF)=0,0
Exp/Cntr=0.3,0.1

Type RM Length L Ch R = 1 ,13801   ,298.8,300,298.2
XS GIS Cut Line= 2
2317982.07598291536765.7076025332318361.52679028537293.454781385
#Sta/Elev= 30
       0 2871.29    52.7 2863.82    63.4 2860.69    81.4 2859.87   127.4 2847.24
   141.6 2844.36   147.5 2842.54   152.1 2841.81   161.6 2841.72   171.8 2838.03
   181.7 2836.02   236.1 2828.45     264 2823.68   270.8 2821.75   284.5 2815.16
   299.9 2810.55   309.7 2806.34   313.5 2805.97   324.5 2804.78   339.3  2805.9
   339.3 2805.91   359.9 2808.11   370.8 2807.08   388.6 2806.66   398.4 2806.57
   425.3 2807.84   482.6 2806.42   534.2 2809.15     560 2809.46     650 2810.08
#Mann= 5 ,-1,0
       0     .06       0     140      .1       0   313.5    .045       0
   339.3     .08       0     560     .05       0
#XS Ineff= 2 , 0
                          467.44         2820.29
Permanent Ineff=
       F       F
Bank Sta=313.5,339.3
XS Rating Curve= 0 ,0
Exp/Cntr(USF)=0,0
Exp/Cntr=0.3,0.1

Type RM Length L Ch R = 1 ,13501   ,293.7,300,299.2
XS GIS Cut Line= 2
2317795.51572894 536981.286231312318151.74502678537524.977952196
#Sta/Elev= 30
       0 2853.69      12  2850.7    52.4 2843.57      62 2842.61    71.6  2840.7
      86  2839.6   104.4 2835.39   148.1  2827.8   199.7 2820.28   205.6 2817.98
   214.2 2813.41   228.6 2802.66   234.4  2799.9   243.8 2798.85     282 2800.19
   312.4 2797.96   320.3 2796.62   330.2  2797.9   339.4 2799.49   372.9 2798.94
   387.2 2797.88   401.6 2798.89   425.5 2798.36   446.4 2800.27   482.9 2802.16
   492.4 2802.03   511.8 2800.08   525.9 2800.02   621.6 2801.53     650 2803.32
#Mann= 5 ,-1,0
       0      .1       0     290     .08       0   312.4    .045       0
   330.2     .08       0     520     .05       0
#XS Ineff= 2 , 0
                          490.99         2805.74
Permanent Ineff=
       F       F
Bank Sta=312.4,330.2
XS Rating Curve= 0 ,0
Exp/Cntr(USF)=0,0
Exp/Cntr=0.3,0.1

Type RM Length L Ch R = 1 ,13201   ,359.7,365.4,366.6
XS GIS Cut Line= 2
2317602.07468786537033.1300583132317834.52252066537640.145712996
#Sta/Elev= 30
       0 2870.33    25.8 2864.15    68.6 2852.22      90 2844.78   115.7 2842.26
   128.6 2838.59   145.7 2836.81   154.2  2833.9   218.5 2819.81   291.3 2807.77
   295.6 2805.75   299.9 2802.58   315.7 2789.39   317.6 2788.41   323.8 2787.71
   338.4 2789.44     347 2789.61   359.8 2791.33   368.4  2790.8     377 2792.56
   424.1 2790.76   438.4 2788.44   449.8  2790.3   462.6  2790.1   471.2 2790.83
   487.9 2790.17   539.7 2793.19   562.3    2793   582.6 2791.88     650 2792.06
#Mann= 5 ,-1,0
       0      .1       0   315.7    .045       0   338.4      .1       0
     460     .08       0     520     .05       0
#XS Ineff= 1 ,-1
  358.14  379.07 2799.18
Permanent Ineff=
       F
Bank Sta=315.7,338.4
XS Rating Curve= 0 ,0
Exp/Cntr(USF)=0,0
Exp/Cntr=0.3,0.1

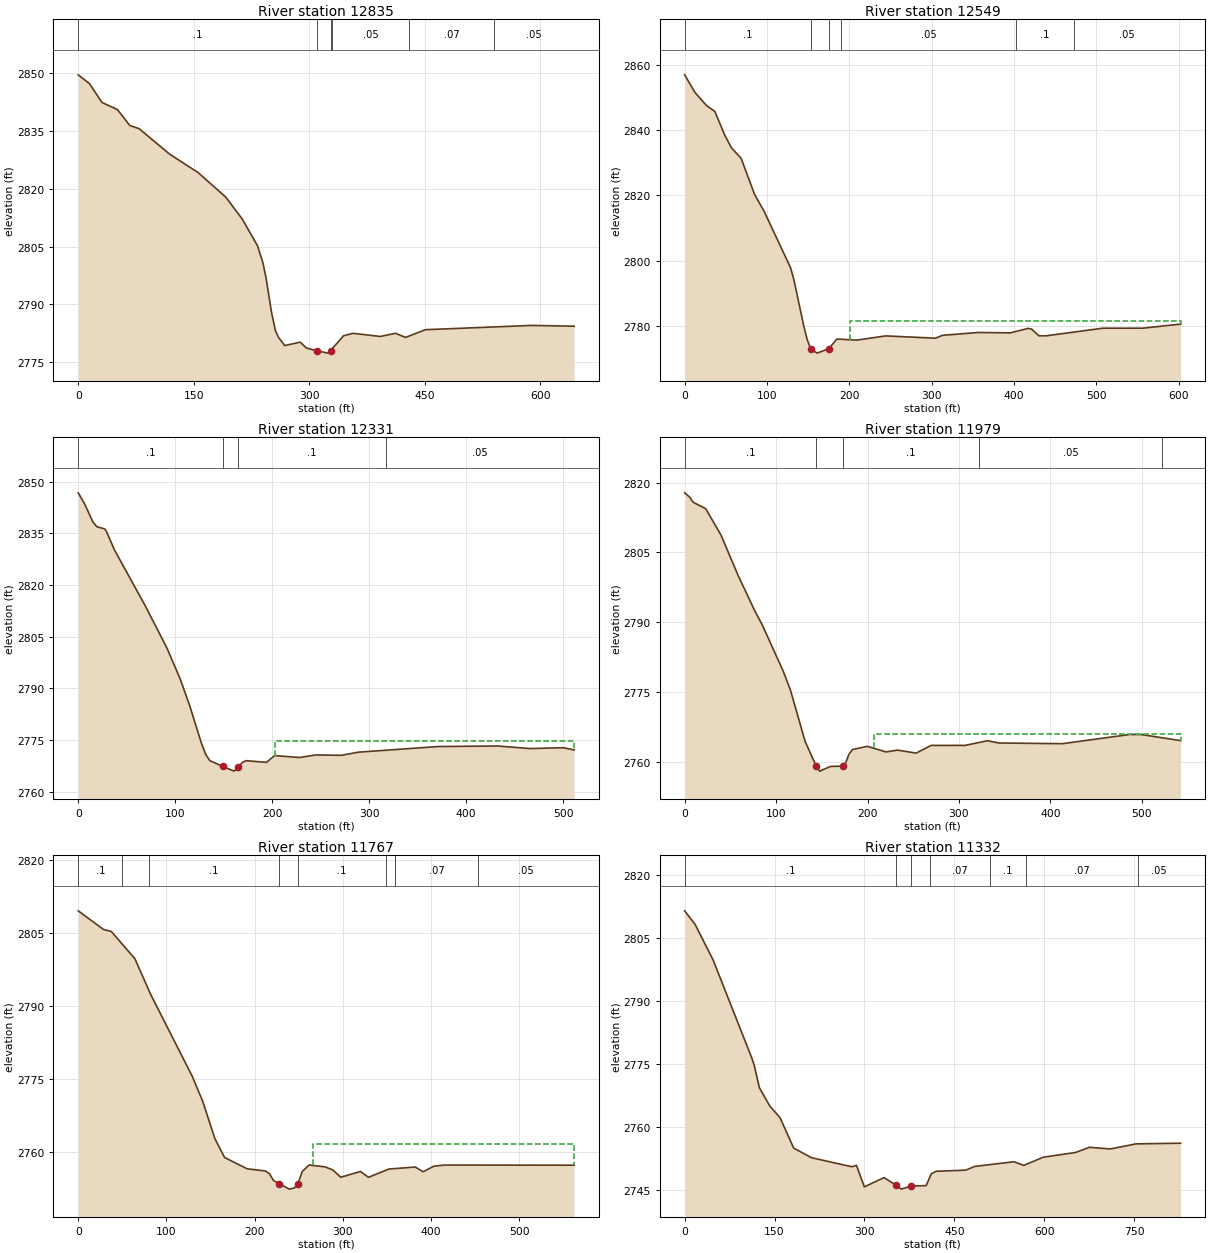
Type RM Length L Ch R = 1 ,12835   ,280.6,286.1,283.6
XS GIS Cut Line= 3
2317379.48550467537190.5432619032317417.32017231537558.120204724
2317522.05168732537811.524956325
#Sta/Elev= 30
       0 2849.62    14.7 2847.32    30.8 2842.44    50.9 2840.59      67 2836.45
    79.1 2835.62   118.7    2829   155.5 2824.23   191.6 2817.83   212.9 2812.14
   232.7 2805.21   239.9 2800.67   243.7 2796.96   250.9  2787.9     256 2783.09
     260 2781.39     268 2779.26   288.2 2780.14   296.2 2778.61   309.3 2777.92
   324.3 2777.29   327.5 2777.95   344.4  2781.8   356.7 2782.44     392 2781.62
   411.8 2782.44   424.8 2781.38   450.7 2783.38   588.4 2784.49   643.7 2784.29
#Mann= 6 ,-1,0
       0      .1       0   309.3    .045       0   327.5      .1       0
     330     .05       0  429.52     .07       0  539.52     .05       0
Bank Sta=309.3,327.5
XS Rating Curve= 0 ,0
Exp/Cntr(USF)=0,0
Exp/Cntr=0.3,0.1

Type RM Length L Ch R = 1 ,12549   ,212.6,217.6,219.2
XS GIS Cut Line= 3
2317183.46935127537232.5505193742317172.30056645537435.029786617
2317325.03421361537804.386257273
#Sta/Elev= 30
       0 2857.03    12.6 2851.58    26.5 2847.62    36.7 2845.77    48.7  2838.5
    56.7 2834.68    68.7 2831.33    84.8 2820.39    96.8 2814.97   128.8 2797.72
   132.8 2793.97   144.8 2779.77   148.9  2775.7153.09212772.905   160.9 2771.58
174.98912772.934   184.9  2775.9   209.4 2775.58   244.1 2776.87   304.7 2776.17
   313.3 2777.05   356.6 2777.92   395.6  2777.8   417.2 2779.17   421.5 2778.98
   430.2  2776.9   438.9 2776.89   508.1 2779.24   556.5 2779.24   602.5 2780.49
#Mann= 6 ,-1,0
       0      .1       0153.0921    .045       0174.9891      .1       0
     190     .05       0  402.79      .1       0  472.79     .05       0
#XS Ineff= 2 , 0
                          200.34          2781.4
Permanent Ineff=
       F       F
Bank Sta=153.0921,174.9891
XS Rating Curve= 0 ,0
Exp/Cntr(USF)=0,0
Exp/Cntr=0.3,0.1

Type RM Length L Ch R = 1 ,12331   ,354.4,352.1,341.8
XS GIS Cut Line= 3
2317012.37916977537214.8515350812316953.98925887537414.127640146
2317068.33153093537695.617404471
#Sta/Elev= 30
       0 2846.75     6.6 2843.55      15 2838.37    19.1 2836.94    27.4 2836.26
    29.2 2835.47    37.5 2830.12    69.1    2814    91.6 2801.68   105.2 2792.74
   114.9 2785.09   126.9 2774.27   131.6  2770.8   135.8 2769.06149.35422767.364
   160.8 2766.02164.9687  2767.1   169.2 2768.52   173.3 2769.05   194.2 2768.56
   202.5 2770.53   228.2 2769.97   245.3 2770.72   271.4  2770.6   288.7 2771.51
   370.7 2773.15   432.7 2773.31   465.7 2772.57   500.3 2772.81   511.5 2772.16
#Mann= 4 ,-1,0
       0      .1       0149.3542    .045       0164.9687      .1       0
  317.65     .05       0
#XS Ineff= 2 , 0
                          203.15         2774.63
Permanent Ineff=
       F       F
Bank Sta=149.3542,164.9687
XS Rating Curve= 0 ,0
Exp/Cntr(USF)=0,0
Exp/Cntr=0.3,0.1

Type RM Length L Ch R = 1 ,11979   ,204.6,212.4,221.4
XS GIS Cut Line= 4
2316692.66732505  537112.5394202 2316645.1973321537209.107890635
 2316647.1226247537293.3255797482316725.18896564537635.190436522
#Sta/Elev= 30
       0 2817.79     5.2 2816.91     9.6 2815.72      23 2814.39    39.7 2808.74
    58.7 2799.95    76.5 2792.54    84.5 2789.59   107.6  2779.6   115.7 2775.44
   131.7 2764.47   143.7 2759.19   147.7 2758.05   159.7 2759.07   173.2 2759.12
   175.7 2759.62   179.7 2761.68   183.7  2762.7   199.9 2763.37   220.4 2762.17
   232.8 2762.56   253.2 2761.92   269.7 2763.58   306.6 2763.57   331.2 2764.58
   343.5 2764.09   413.1 2763.94   487.1 2765.92   499.9 2765.89   542.5  2764.6
#Mann= 5 ,-1,0
       0      .1       0   143.7    .045       0   173.2      .1       0
  321.84     .05       0  521.84     .07       0
#XS Ineff= 2 , 0
                          207.21         2766.12
Permanent Ineff=
       F       F
Bank Sta=143.7,173.2
XS Rating Curve= 0 ,0
Exp/Cntr(USF)=0,0
Exp/Cntr=0.3,0.1

Type RM Length L Ch R = 1 ,11767   ,444.8,434.6,419.9
XS GIS Cut Line= 4
2316620.66210735537082.7951052752316471.57264863537162.692779266
  2316374.803452537353.6506606062316340.11056472537529.047324469
#Sta/Elev= 30
       0 2809.52    28.7 2805.68    37.6 2805.27    64.3 2799.66    82.2 2792.31
   129.2 2775.53     141 2770.42   154.9  2762.7   165.9 2758.83   191.4 2756.51
   212.2 2756.06   216.8  2755.5   221.3  2754.1228.05712753.433   239.2 2752.33
     245 2752.58   248.9 2753.44   253.9 2755.95   261.6 2757.29   279.6 2756.91
   288.5 2756.27   297.5 2754.77   319.9 2755.96   328.9 2754.76   352.1 2756.46
   381.9 2756.87   390.9  2755.9   403.1 2757.05   415.4 2757.28     562 2757.25
#Mann= 8 ,-1,0
       0      .1       0      50     .12       0      80      .1       0
228.0571    .045       0   248.9      .1       0  349.15     .05       0
  359.15     .07       0  453.23     .05       0
#XS Ineff= 2 , 0
                          265.69         2761.53
Permanent Ineff=
       F       F
Bank Sta=228.0571,248.9
XS Rating Curve= 0 ,0
Exp/Cntr(USF)=0,0
Exp/Cntr=0.3,0.1

Type RM Length L Ch R = 1 ,11332   ,363.3,368.1,363.7
XS GIS Cut Line= 5
2316154.09840543536760.9129018842316056.35819097 537012.34193576
2316094.67879284537157.4957306972316274.16348751537353.650660607
2316282.64652195537495.229865934
#Sta/Elev= 30
       0 2811.39    17.5 2808.14    47.5  2799.7   111.9 2776.47   116.2 2774.62
   124.7 2769.35   141.9 2765.05   159.1 2762.25   181.9 2755.02   211.8 2752.73
   278.9 2750.59   286.7 2750.91   299.8 2745.81   332.7 2748.01   353.4 2746.14
   361.6 2745.27     378 2746.01     403  2746.1   411.3 2748.86   419.6 2749.51
   468.9 2749.78   484.5 2750.68   549.6 2751.78   565.8 2750.91   598.4 2752.85
   652.6 2753.99   675.5 2755.21   709.9 2754.81   753.4 2756.02   827.6 2756.18
#Mann= 7 ,-1,0
       0      .1       0   353.4    .045       0     378      .1       0
  409.76     .07       0  509.89      .1       0  569.89     .07       0
  755.76     .05       0
Bank Sta=353.4,378
XS Rating Curve= 0 ,0
Exp/Cntr(USF)=0,0
Exp/Cntr=0.3,0.1

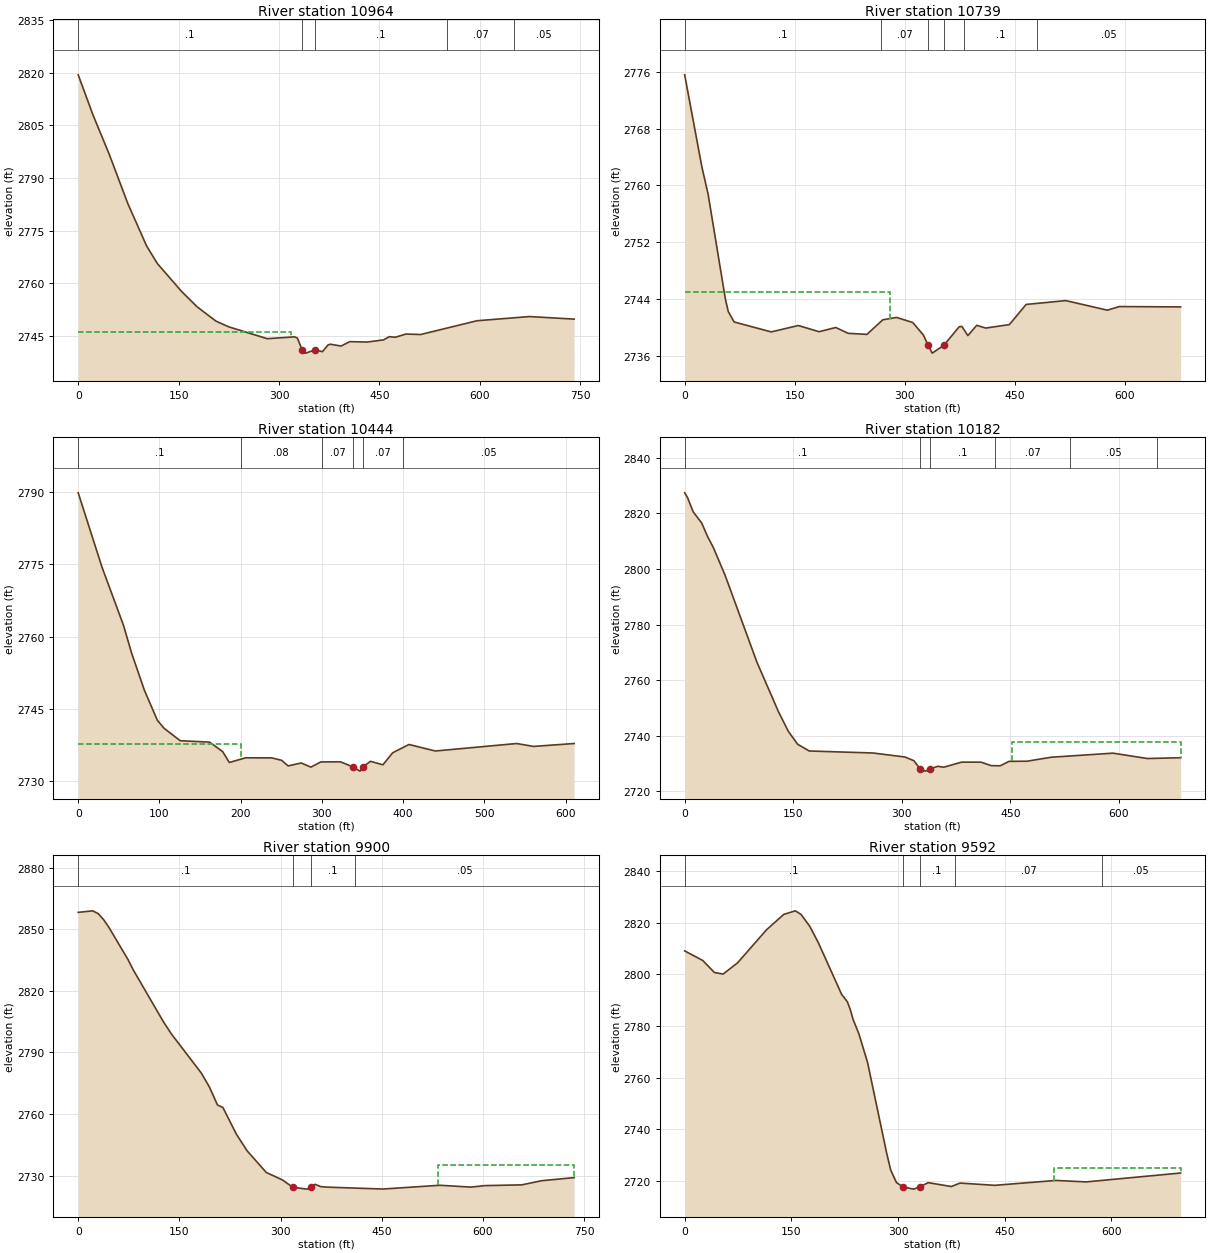
Type RM Length L Ch R = 1 ,10964   ,224.1,225.6,226.4
XS GIS Cut Line= 4
2315805.01038505536795.0155074192315816.01925851537094.966104138
2315870.88610982537287.8850329372315994.61422115537493.780402978
#Sta/Elev= 30
       0 2819.41    22.2  2807.9    46.2 2796.82    74.2 2782.66   102.2  2770.6
   118.2  2765.6   154.3 2757.66   177.6 2753.25   205.9 2749.16   225.2 2747.52
   282.4 2744.16   323.2 2744.68   327.4 2744.34   334.4 2741.02   339.9 2740.04
   353.9 2740.98   364.8 2740.45   373.1 2742.35   376.5 2742.59   392.7 2742.06
   405.7 2743.32   431.6  2743.2   456.3 2743.82   464.6 2744.73   473.7 2744.57
   489.6 2745.48   511.6 2745.35   595.9 2749.28   674.1 2750.47   740.9 2749.74
#Mann= 5 ,-1,0
       0      .1       0   334.4    .045       0   353.9      .1       0
  550.72     .07       0  650.72     .05       0
#XS Ineff= 2 , 0
          317.72 2746.14
Permanent Ineff=
       F       F
Bank Sta=334.4,353.9
XS Rating Curve= 0 ,0
Exp/Cntr(USF)=0,0
Exp/Cntr=0.3,0.1

Type RM Length L Ch R = 1 ,10739   ,293.1,294.4,292.4
XS GIS Cut Line= 4
2315470.89245322536893.7572158352315472.65727399536971.050709065
2315609.82503246537120.6877798422315669.40825625537511.901185601
#Sta/Elev= 30
       0 2775.57    23.4 2762.62      32 2758.72    55.4 2744.03    59.4 2742.22
    67.4 2740.75     118 2739.35   154.9 2740.25   183.2 2739.38   205.9 2739.97
   222.9 2739.15   248.4    2739   270.1 2741.06   288.9 2741.39   310.9 2740.67
   325.3 2738.92331.63452737.506   337.4 2736.36353.43432737.473   374.1 2740.07
   377.9 2740.12     386 2738.83   398.1 2740.28   410.3 2739.89   442.6 2740.38
   465.4 2743.22   519.5 2743.76   576.2 2742.41   592.4 2742.92     676 2742.87
#Mann= 6 ,-1,0
       0      .1       0  267.31     .07       0331.6345    .045       0
353.4343     .07       0  380.31      .1       0  480.31     .05       0
#XS Ineff= 2 , 0
             280    2745
Permanent Ineff=
       F       F
Bank Sta=331.6345,353.4343
XS Rating Curve= 0 ,0
Exp/Cntr(USF)=0,0
Exp/Cntr=0.3,0.1

Type RM Length L Ch R = 1 ,10444   ,262,262.4,258.9
XS GIS Cut Line= 3
2315308.76346253  536928.29455412315358.74797481537391.091232557
2315438.09805488537512.520260861
#Sta/Elev= 30
       0  2789.8    29.3 2774.39    55.8 2762.32    65.6 2756.66    81.4 2748.93
    97.4 2742.68   105.6 2741.03   125.6 2738.44   161.8 2738.15   177.9 2736.17
     186 2733.93   206.1  2734.9   238.3 2734.88   250.3 2734.39   258.4 2733.22
   274.5 2733.83   286.5 2732.97   298.6 2734.04   322.8 2734.07     338 2733.03
   346.9 2732.14   350.9 2733.04   359.7 2734.18   375.1 2733.45   387.1 2735.94
   407.2 2737.66   439.6 2736.31   539.7 2737.86   560.5 2737.26   610.5 2737.86
#Mann= 6 ,-1,0
       0      .1       0     200     .08       0     300     .07       0
     338    .045       0   350.9     .07       0     400     .05       0
#XS Ineff= 2 , 0
           200.2 2737.72
Permanent Ineff=
       F       F
Bank Sta=338,350.9
XS Rating Curve= 0 ,0
Exp/Cntr(USF)=0,0
Exp/Cntr=0.3,0.1

Type RM Length L Ch R = 1 ,10182   ,280.1,281.5,281.9
XS GIS Cut Line= 4
2315091.07769576536897.4165551062315108.42716918537195.415458636
2315157.33819193537404.227901882 2315254.6204555537546.332831972
#Sta/Elev= 30
       0 2827.37     3.8 2825.75    11.8 2820.52    23.5 2816.53    31.8 2811.57
    39.8 2807.59    55.9  2797.7    99.9 2766.44   129.5 2748.73   143.2 2741.62
     156    2737   172.1 2734.56   260.2 2733.84   304.4 2732.39   316.7 2731.07
     325 2728.21   332.5 2727.32   338.8 2728.08   349.6 2729.06   357.8 2728.72
   382.5 2730.55   409.6 2730.54   423.6 2729.29   435.9 2729.24   448.2 2730.84
   472.9 2730.88   506.1 2732.31   591.7 2733.78   639.4 2731.85   685.2 2732.14
#Mann= 6 ,-1,0
       0      .1       0     325    .045       0   338.8      .1       0
   428.5     .07       0  532.97     .05       0  652.97     .07       0
#XS Ineff= 2 , 0
                          452.44         2737.89
Permanent Ineff=
       F       F
Bank Sta=325,338.8
XS Rating Curve= 0 ,0
Exp/Cntr(USF)=0,0
Exp/Cntr=0.3,0.1

Type RM Length L Ch R = 1 ,9900    ,308.5,307.8,305.4
XS GIS Cut Line= 3
2314805.49065257536911.7793200652314858.89606664537448.412792413
2314917.33740104537635.346857943
#Sta/Elev= 30
       0  2858.2    21.5 2858.95    29.5  2857.6    37.6 2854.69    45.6 2850.85
    73.8 2835.21    81.8 2830.06     126 2805.08   138.1    2799   182.3    2780
   194.4  2773.2   206.4  2764.4   214.5 2763.12   234.6 2750.08   250.6 2741.97
   278.8 2731.51   302.9 2727.85   318.1  2724.3   339.1  2723.4  344.932724.233
   351.1 2725.75   359.2 2724.64   367.2 2724.39   451.6 2723.45     536 2725.28
     582 2724.39     603 2725.11   657.4 2725.48   686.8 2727.49   735.1 2729.01
#Mann= 4 ,-1,0
       0      .1       0   318.1    .045       0  344.93      .1       0
     410     .05       0
#XS Ineff= 2 , 0
                          532.89         2735.02
Permanent Ineff=
       F       F
Bank Sta=318.1,344.93
XS Rating Curve= 0 ,0
Exp/Cntr(USF)=0,0
Exp/Cntr=0.3,0.1

Type RM Length L Ch R = 1 ,9592    ,257.8,255.3,253.4
XS GIS Cut Line= 3
2314483.34634502536944.061620326 2314576.3300125537462.605607918
2314642.98919739537619.643374365
#Sta/Elev= 30
       0 2809.06    25.5 2805.34    41.8 2800.71      54 2800.09    74.3 2804.42
   114.9 2817.16   139.3 2823.16   155.6 2824.55   163.6 2823.17   175.9 2818.57
   188.1 2812.15   220.6 2792.31   228.7 2789.42   232.6 2786.62   236.8 2782.59
     245 2776.97   257.2  2765.9   284.2 2730.66   289.7 2724.33   297.8 2719.48
   307.4 2717.75     322 2716.94   330.3 2717.81   342.5 2719.44     375 2717.95
   387.2 2719.28   436.1 2718.41     522  2720.3   564.4 2719.73   697.4 2723.17
#Mann= 5 ,-1,0
       0      .1       0   307.4    .045       0   330.3      .1       0
     380     .07       0  586.81     .05       0
#XS Ineff= 2 , 0
                             520            2725
Permanent Ineff=
       F       F
Bank Sta=307.4,330.3
XS Rating Curve= 0 ,0
Exp/Cntr(USF)=0,0
Exp/Cntr=0.3,0.1

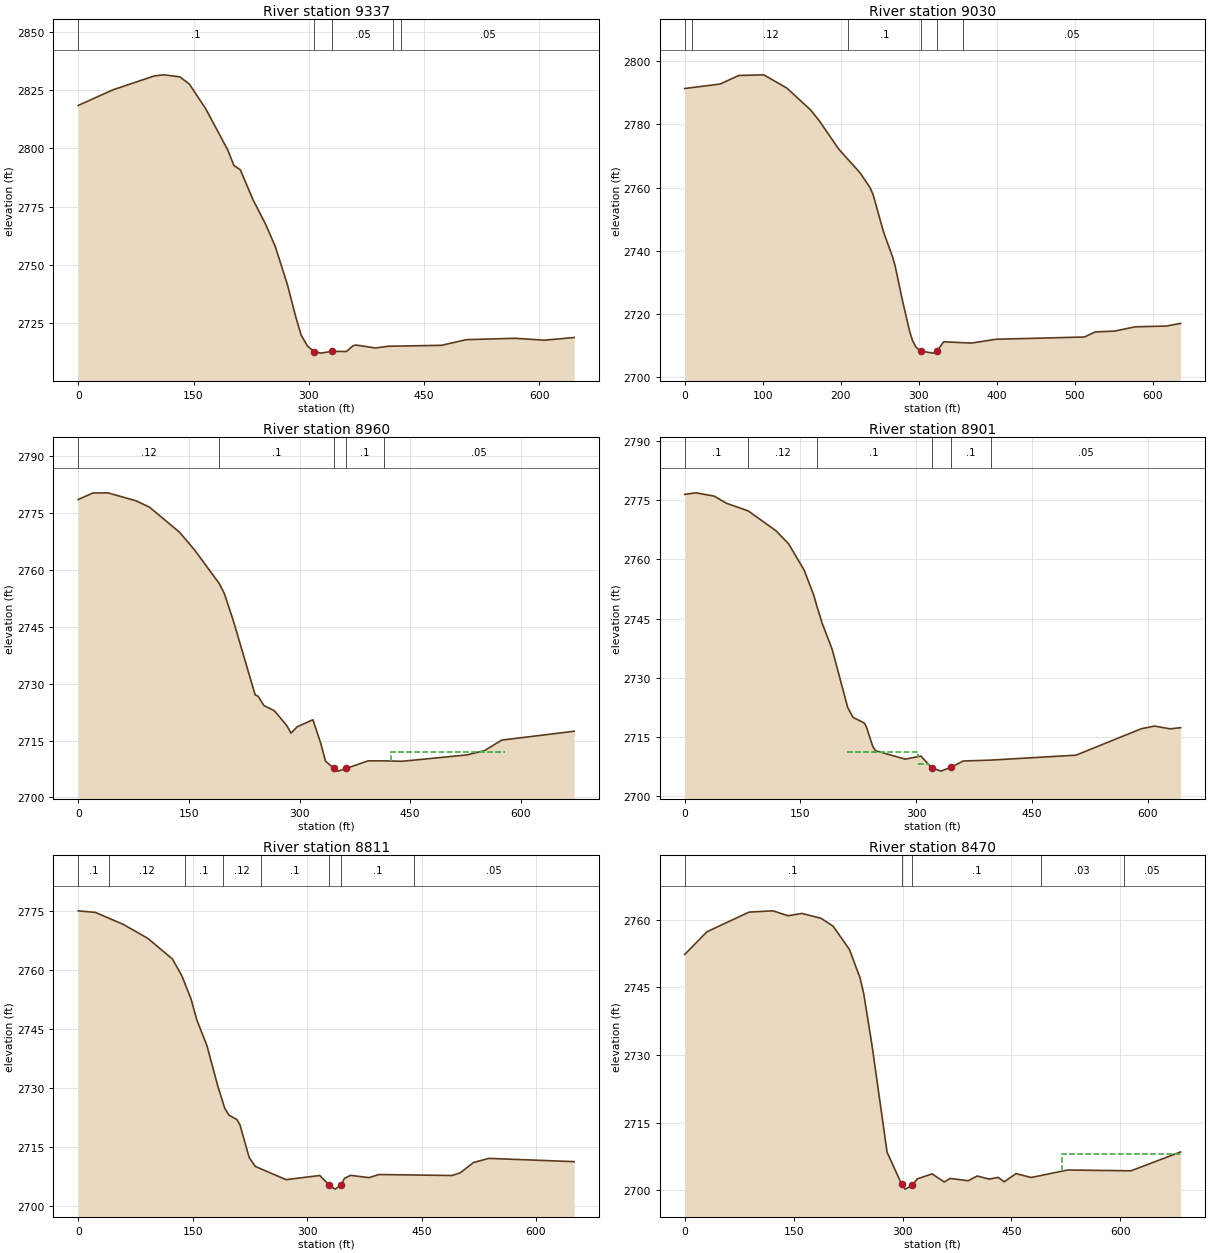
Type RM Length L Ch R = 1 ,9337    ,309.6,307.4,305.8
XS GIS Cut Line= 3
2314209.04474887537013.4283275962314278.44108256537273.807749689
2314397.92133471537629.924871525
#Sta/Elev= 30
       0 2818.44    45.3 2825.15    99.1 2831.12   111.5 2831.58   132.2 2830.71
   144.6 2827.59   165.8 2817.06   194.3 2799.45   202.6 2792.62   210.9 2790.81
   227.4 2777.94   243.6 2767.55   256.4 2757.84   272.1 2741.56     283 2727.66
   289.9 2719.89   298.3 2715.11   306.8 2712.79   315.2 2712.11 330.3642712.887
     349  2712.8   357.4 2715.29   361.6 2715.58   386.9 2714.31     403 2715.06
   472.5 2715.46   505.1  2717.9   568.4 2718.48   606.3 2717.66   645.1 2718.81
#Mann= 5 ,-1,0
       0      .1       0   306.8    .045       0 330.364     .05       0
  409.47     .07       0  419.47     .05       0
Bank Sta=306.8,330.364
XS Rating Curve= 0 ,0
Exp/Cntr(USF)=0,0
Exp/Cntr=0.3,0.1

Type RM Length L Ch R = 1 ,9030    ,74.1,70,66.5
BEGIN DESCRIPTION:
Structure XS 4
END DESCRIPTION:
XS GIS Cut Line= 4
2313979.11230091537111.8062613622313985.93607395537378.311979762
2314091.60803666537595.4620569882314176.45122014537690.945900738
#Sta/Elev= 30
       0 2791.36    45.4 2792.77    69.4 2795.49   101.4 2795.69   131.1 2791.48
   161.4 2784.58   172.8 2781.08   197.4 2772.22   224.8  2764.7   237.5 2760.04
   241.5 2757.83   254.9    2746   266.6 2738.02   269.8 2735.22   279.4 2724.07
   288.4 2714.53     292  2711.7   296.5 2709.54   302.6 2708.26   318.7 2707.63
   323.2 2708.23   332.1 2711.22   367.6 2710.81   399.1 2712.02   512.5 2712.73
   526.4 2714.34   551.1  2714.6   577.7 2715.96   617.4 2716.19   635.8 2717.04
#Mann= 6 ,-1,0
       0      .1       0      10     .12       0     210      .1       0
   302.6    .045       0   323.2      .1       0  356.59     .05       0
Bank Sta=302.6,323.2
XS Rating Curve= 0 ,0
Exp/Cntr(USF)=0,0
Exp/Cntr=0.5,0.3

Type RM Length L Ch R = 1 ,8960    ,61.2,58.6,56
BEGIN DESCRIPTION:
Structure XS 3; 13.9 ft between structure and xs
END DESCRIPTION:
XS GIS Cut Line= 6
 2313894.2144492537157.4712193292313857.98748352537394.600168736
2313891.67595633537429.5787207022313921.25678266537427.867433229
2313963.06109093537499.0080981822314137.95808873537701.952514448
#Sta/Elev= 30
       0 2778.64    19.9 2780.35    40.2  2780.4    78.4 2778.29    96.8  2776.6
   137.3 2770.01   157.5 2765.38   191.1 2756.47     198 2753.85   210.1 2746.74
   239.9 2727.05   243.5 2726.76   251.7 2724.26   266.1 2722.84   282.9 2718.91
   288.4 2716.97   296.9 2718.66   318.1  2720.5   328.5 2714.43   335.2 2709.59
   346.7 2707.66   352.2 2706.94   363.6 2707.67   392.9 2709.65   413.8 2709.66
   439.2 2709.54   527.3 2711.23   550.7 2712.35     574 2715.13   672.2 2717.47
#Mann= 5 ,-1,0
       0     .12       0   191.1      .1       0   346.7    .045       0
   363.6      .1       0   413.8     .05       0
#XS Ineff= 3 ,-1
       0     333    2708     376  424.11  2707.3  424.11  578.07 2712.05
Permanent Ineff=
       F       F       F
Bank Sta=346.7,363.6
XS Rating Curve= 0 ,0
Exp/Cntr(USF)=0,0
Exp/Cntr=0.5,0.3

Type RM Length L Ch R = 1 ,8901    ,77,90.4,104.8
BEGIN DESCRIPTION:
Structure XS 2; 8.8 ft between structure and xs
END DESCRIPTION:
XS GIS Cut Line= 4
 2313862.5254686537175.2385846592313835.37576955537426.030179911
2314092.96281289537673.570878921 2314109.5764532537701.952514448
#Sta/Elev= 30
       0 2776.55    14.8 2776.94    38.2  2776.1    54.3 2774.28    82.4 2772.34
   118.6 2767.24   134.6 2763.98   154.8 2757.28   167.3 2750.87     171 2748.29
   178.2 2743.74   191.1 2737.13   211.2 2722.37   218.1 2719.86   232.6 2718.45
   235.3 2717.52   243.5 2712.55   247.1 2711.41   285.7 2709.25     306 2710.05
   319.9 2707.07   331.8 2706.21   345.6 2707.23   360.7 2708.78   396.5 2709.01
   506.8 2710.26   591.7    2717   608.7 2717.66   629.1 2716.95   642.4 2717.26
#Mann= 6 ,-1,0
       0      .1       0    82.4     .12       0     171      .1       0
   319.9    .045       0   345.6      .1       0   396.5     .05       0
#XS Ineff= 3 ,-1
  210.13  302.22 2711.17  302.22     316    2708     348   642.4  2707.3
Permanent Ineff=
       F       F       F
Bank Sta=319.9,345.6
XS Rating Curve= 0 ,0
Exp/Cntr(USF)=0,0
Exp/Cntr=0.5,0.3

Type RM Length L Ch R = 1 ,8811    ,337.4,340.4,339.6
BEGIN DESCRIPTION:
Structure XS 1
END DESCRIPTION:
XS GIS Cut Line= 2
2313848.74502915537182.6077606662313773.70516376537828.261707143
#Sta/Elev= 30
       0 2775.03    22.7 2774.62      59 2771.59    91.2 2768.04   123.4 2762.81
   135.5 2758.68   147.6  2752.8   155.6 2747.26   168.8 2740.74   183.2 2730.37
   191.9 2724.98   197.6 2723.14     208 2722.02     212 2720.67   224.1 2712.37
   232.1 2710.11   272.4 2706.76   316.7 2707.81   328.8 2705.42   336.8 2704.35
   344.9 2705.43   348.9 2707.09     357 2707.85   381.1 2707.27   394.1 2708.06
   489.9 2707.81   500.7 2708.49     518  2711.1   538.2 2712.16     650 2711.33
#Mann= 8 ,-1,0
       0      .1       0      40     .12       0     140      .1       0
     190     .12       0     240      .1       0   328.8    .045       0
   344.9      .1       0     440     .05       0
Bank Sta=328.8,344.9
XS Rating Curve= 0 ,0
Exp/Cntr(USF)=0,0
Exp/Cntr=0.3,0.1

Type RM Length L Ch R = 1 ,8470    ,251.4,251.3,250.4
XS GIS Cut Line= 3
2313663.51973392  537039.56141822313533.05623374537537.400539013
2313599.79936741537691.864369124
#Sta/Elev= 30
       0 2752.27    30.6 2757.29    88.5 2761.65   121.6 2761.94   142.3 2760.85
   161.3 2761.36   187.5 2760.31   204.3 2758.56   226.9 2753.37   241.5 2747.07
   246.5 2743.62     258 2732.11   278.7 2708.46   298.9 2701.31   303.5 2700.28
313.69952701.136   320.1 2702.54   340.7 2703.66   357.3 2701.87   365.6 2702.65
   390.4 2702.14   402.8 2703.19   419.3  2702.5   431.7 2702.88     440  2701.9
   456.2 2703.71   477.2 2702.86   527.5 2704.52   614.6 2704.34   682.9 2708.52
#Mann= 5 ,-1,0
       0      .1       0   298.9    .045       0313.6995      .1       0
     490     .03       0  604.65     .05       0
#XS Ineff= 2 , 0
                             520            2708
Permanent Ineff=
       F       F
Bank Sta=298.9,313.6995
XS Rating Curve= 0 ,0
Exp/Cntr(USF)=0,0
Exp/Cntr=0.3,0.1