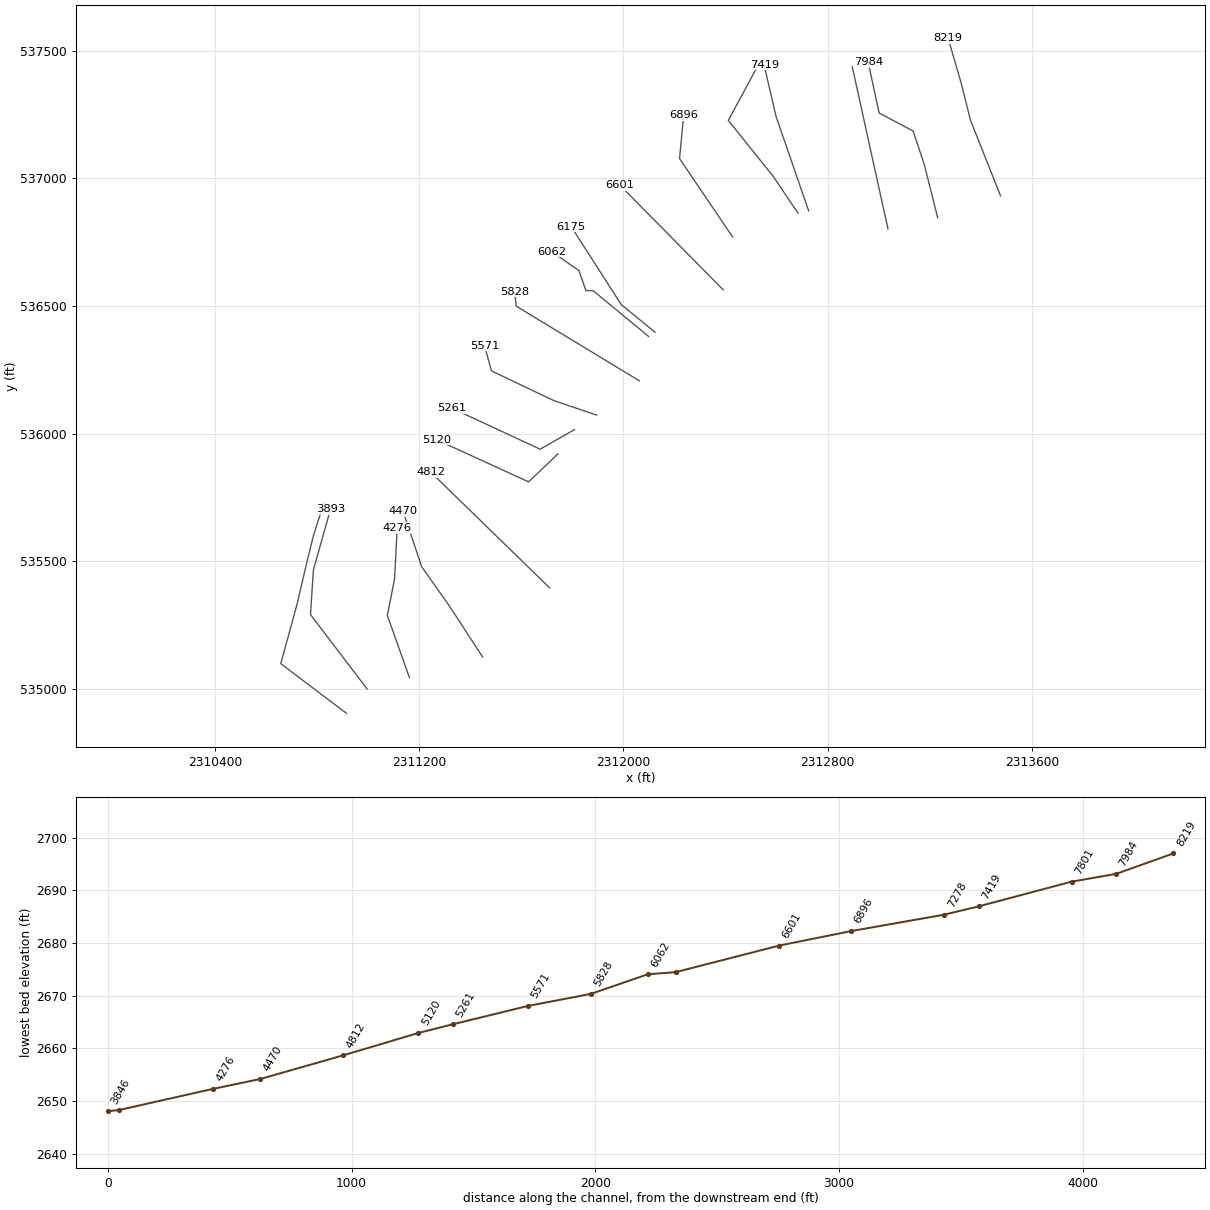
HEC-RAS study BFFLRN.prj: BFFLRN

--- BFFLRN.g01 (geometry) --- (continued)

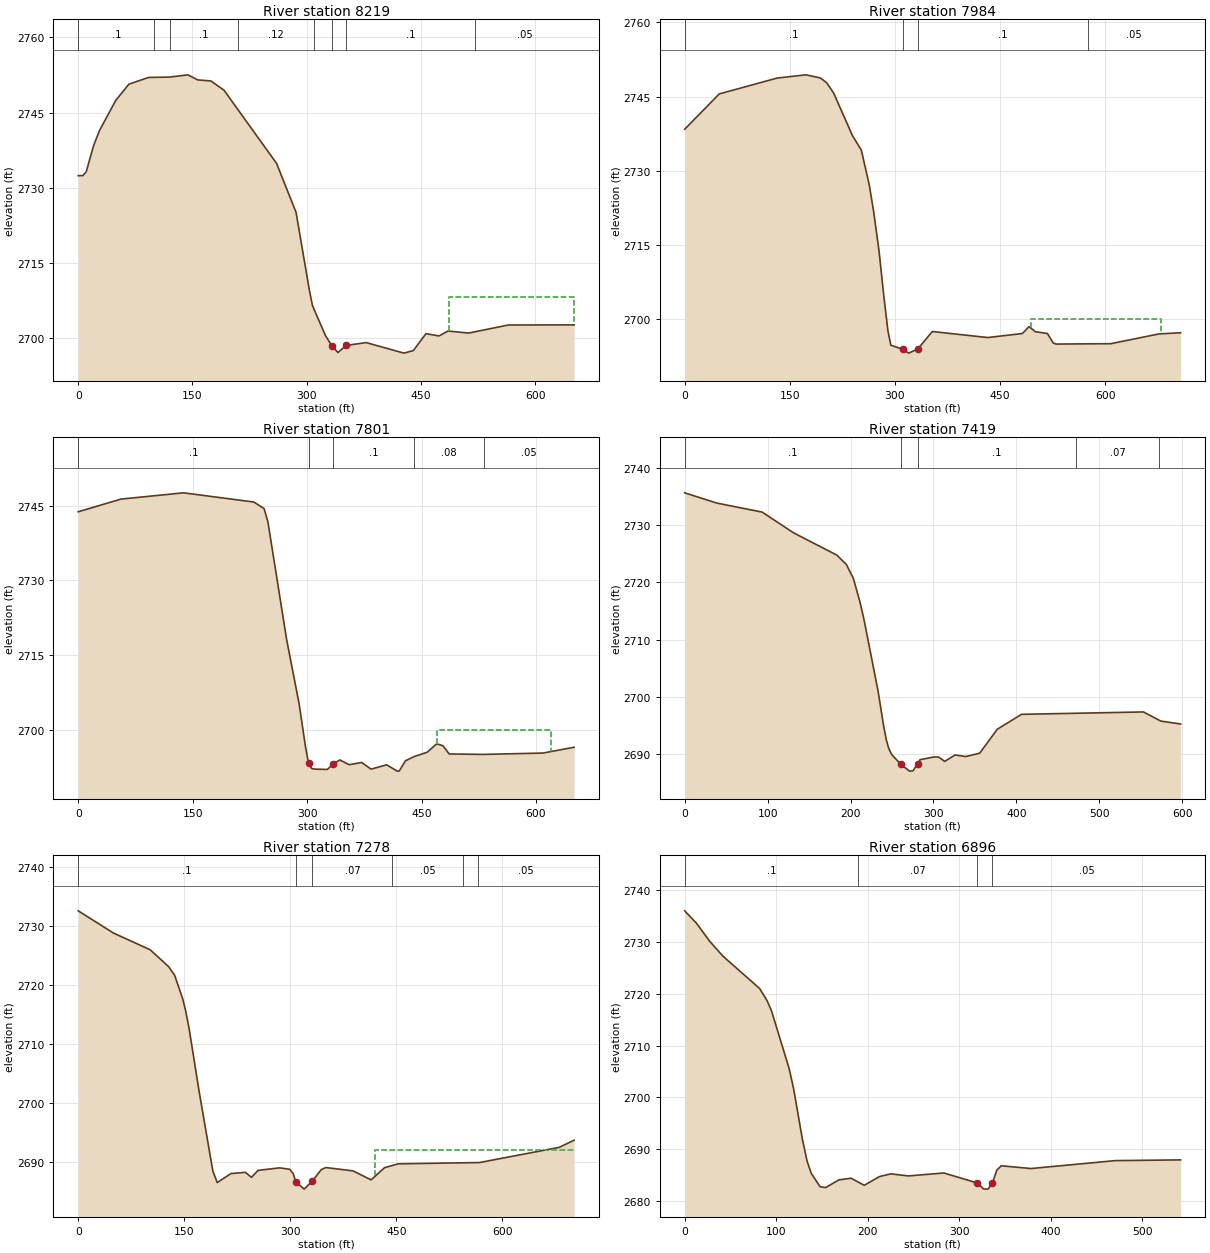
Type RM Length L Ch R = 1 ,8219    ,234.4,235.4,235.3
XS GIS Cut Line= 4
2313476.51412073536931.3653117822313358.87167982537227.352033027
2313321.71230831537374.8282886832313271.46983648537548.177148159
#Sta/Elev= 30
       0 2732.42     6.3 2732.43    10.6 2733.24    20.1 2738.37    27.8 2741.37
    49.3 2747.43    66.5 2750.66    92.3 2752.01     120 2752.08     144 2752.53
   156.9 2751.52   174.2 2751.31   191.3 2749.48   260.4 2734.88     286 2725.11
   303.5 2709.56   307.6 2706.49   324.5 2700.56   332.8 2698.53     341 2697.15
   351.9 2698.57   378.1 2699.13   427.6 2697.03     440 2697.54   456.5 2700.91
   473.7 2700.46   485.5 2701.44   512.5 2701.03   564.7 2702.64   651.1 2702.66
#Mann= 8 ,-1,0
       0      .1       0     100     .12       0     120      .1       0
     210     .12       0     310      .1       0   332.8    .045       0
   351.9      .1       0  520.59     .05       0
#XS Ineff= 2 , 0
                          487.21         2708.27
Permanent Ineff=
       F       F
Bank Sta=332.8,351.9
XS Rating Curve= 0 ,0
Exp/Cntr(USF)=0,0
Exp/Cntr=0.3,0.1

Type RM Length L Ch R = 1 ,7984    ,184.4,183,181.9
XS GIS Cut Line= 5
2313230.39355686536845.3934977222313176.98850244 537057.71115311
2313134.00394644537185.3622588042313001.14259153537255.700623165
2312958.15803554537454.992655523
#Sta/Elev= 30
       0  2738.4    49.3 2745.55   131.8 2748.75     173 2749.41   193.6 2748.78
   202.7 2747.81   212.6 2745.73   239.5 2737.11   252.1  2734.2   263.4 2727.19
   269.7 2721.78   277.5 2713.68   284.2 2704.69   290.1 2697.62   294.3 2694.73
   311.2 2693.94   319.7 2693.14   332.8    2694   353.4 2697.51   432.6 2696.29
   482.1 2697.11   491.5  2698.5   500.5 2697.47   517.7 2697.11   525.9 2695.21
     530 2694.97     575 2695.02   607.8 2695.04   676.8 2697.02   707.8 2697.26
#Mann= 4 ,-1,0
       0      .1       0   311.2    .045       0   332.8      .1       0
     575     .05       0
#XS Ineff= 1 ,-1
  493.92   679.6 2700.11
Permanent Ineff=
       F
Bank Sta=311.2,332.8
XS Rating Curve= 0 ,0
Exp/Cntr(USF)=0,0
Exp/Cntr=0.3,0.1

Type RM Length L Ch R = 1 ,7801    ,378.4,381.5,381
XS GIS Cut Line= 2
 2313035.6232328536802.3520499432312895.81448576537437.138245642
#Sta/Elev= 30
       0 2743.77    56.1 2746.32   138.1 2747.58   230.2 2745.73   243.6 2744.42
   248.6 2741.77   273.2 2718.07   289.6 2705.13   297.8 2696.63   301.9 2693.23
     306 2692.18   310.7 2692.06   326.5    2692   334.2 2693.07   342.9 2693.91
   355.1 2692.95   371.5  2693.4   383.8 2692.06   404.3 2692.93   418.1 2691.66
   420.7 2691.67   428.9 2693.74   440.4 2694.59   457.5 2695.46   469.8 2697.14
     478 2696.78   486.2 2695.11   531.3 2695.02   609.1 2695.29     650 2696.46
#Mann= 5 ,-1,0
       0      .1       0   301.9    .045       0   334.2      .1       0
   440.4     .08       0   531.3     .05       0
#XS Ineff= 1 ,-1
     470     620    2700
Permanent Ineff=
       T
Bank Sta=301.9,334.2
XS Rating Curve= 0 ,0
Exp/Cntr(USF)=0,0
Exp/Cntr=0.3,0.1

Type RM Length L Ch R = 1 ,7419    ,138.4,140.8,150.4
XS GIS Cut Line= 3
2312725.19497834536872.8556481042312597.10456399 537243.60925806
2312550.79263833537444.145383547
#Sta/Elev= 30
       0 2735.68    38.4  2733.9    93.4 2732.31   131.5 2728.66   183.5 2724.78
     195 2723.14   203.5 2720.68   211.4 2716.56   216.2 2713.54   233.1 2701.09
   240.1 2694.73   243.2 2692.44   245.8 2691.07   249.5  2689.9   260.4  2688.2
   271.2 2686.97   275.4 2687.03     281 2688.27   283.9 2688.97   300.8 2689.45
   306.2 2689.44   313.5 2688.67   326.2  2689.8   338.9 2689.52   355.8 2690.11
     377  2694.3   406.2 2696.91   553.3 2697.33   574.2 2695.73   598.1 2695.22
#Mann= 5 ,-1,0
       0      .1       0   260.4    .045       0     281      .1       0
  472.26     .07       0  572.26     .05       0
Bank Sta=260.4,281
XS Rating Curve= 0 ,0
Exp/Cntr(USF)=0,0
Exp/Cntr=0.3,0.1

Type RM Length L Ch R = 1 ,7278    ,377,381.9,359.9
XS GIS Cut Line= 4
2312683.69780975536863.4118946612312586.30733277537007.881948458
2312410.70618915537226.7981261452312527.79654682537443.749081378
#Sta/Elev= 30
       0 2732.62    49.9 2728.85   101.8 2726.01     128 2723.13   136.4 2721.68
   147.9 2717.65   151.7 2715.78   156.6 2712.82   170.9 2702.06   190.4 2688.47
   196.6 2686.51     216 2688.04   236.4 2688.25     245  2687.4   254.4 2688.58
   284.8 2689.01   299.1 2688.77   304.1 2688.04   307.6 2686.68   319.5  2685.4
   331.1 2686.76   343.8 2688.72   350.2 2689.06   388.6  2688.5   414.2 2686.97
   433.3 2689.04   452.5 2689.69   567.5 2689.91   680.3 2692.49   701.4 2693.71
#Mann= 6 ,-1,0
       0      .1       0   307.6    .045       0   331.1     .07       0
  444.23     .05       0  544.87     .07       0  564.87     .05       0
#XS Ineff= 2 , 0
                             420            2692
Permanent Ineff=
       F       F
Bank Sta=307.6,331.1
XS Rating Curve= 0 ,0
Exp/Cntr(USF)=0,0
Exp/Cntr=0.3,0.1

Type RM Length L Ch R = 1 ,6896    ,293,295.5,296.5
XS GIS Cut Line= 3
2312427.51213788536770.5839017562312219.70469715537077.553316652
2312235.96192218537248.254179498
#Sta/Elev= 30
       0 2736.06    12.8 2733.69    27.3 2730.19    41.7 2727.32      82 2721.04
    90.1  2718.7    94.9 2716.75   114.2 2705.59   119.1 2701.69   128.7 2691.91
   133.9 2687.65   138.4 2685.33     148 2682.75   154.1 2682.58   168.5 2684.06
   181.9 2684.39   196.3 2683.02   212.9  2684.7   225.3 2685.23   244.7 2684.83
   283.3  2685.4   319.9 2683.47   326.8 2682.31   331.6 2682.28   336.4 2683.48
   341.3 2685.95   346.1 2686.79   378.6 2686.26   470.8 2687.79   542.2 2687.93
#Mann= 4 ,-1,0
       0      .1       0     190     .07       0   319.9    .045       0
   336.4     .05       0
Bank Sta=319.9,336.4
XS Rating Curve= 0 ,0
Exp/Cntr(USF)=0,0
Exp/Cntr=0.3,0.1

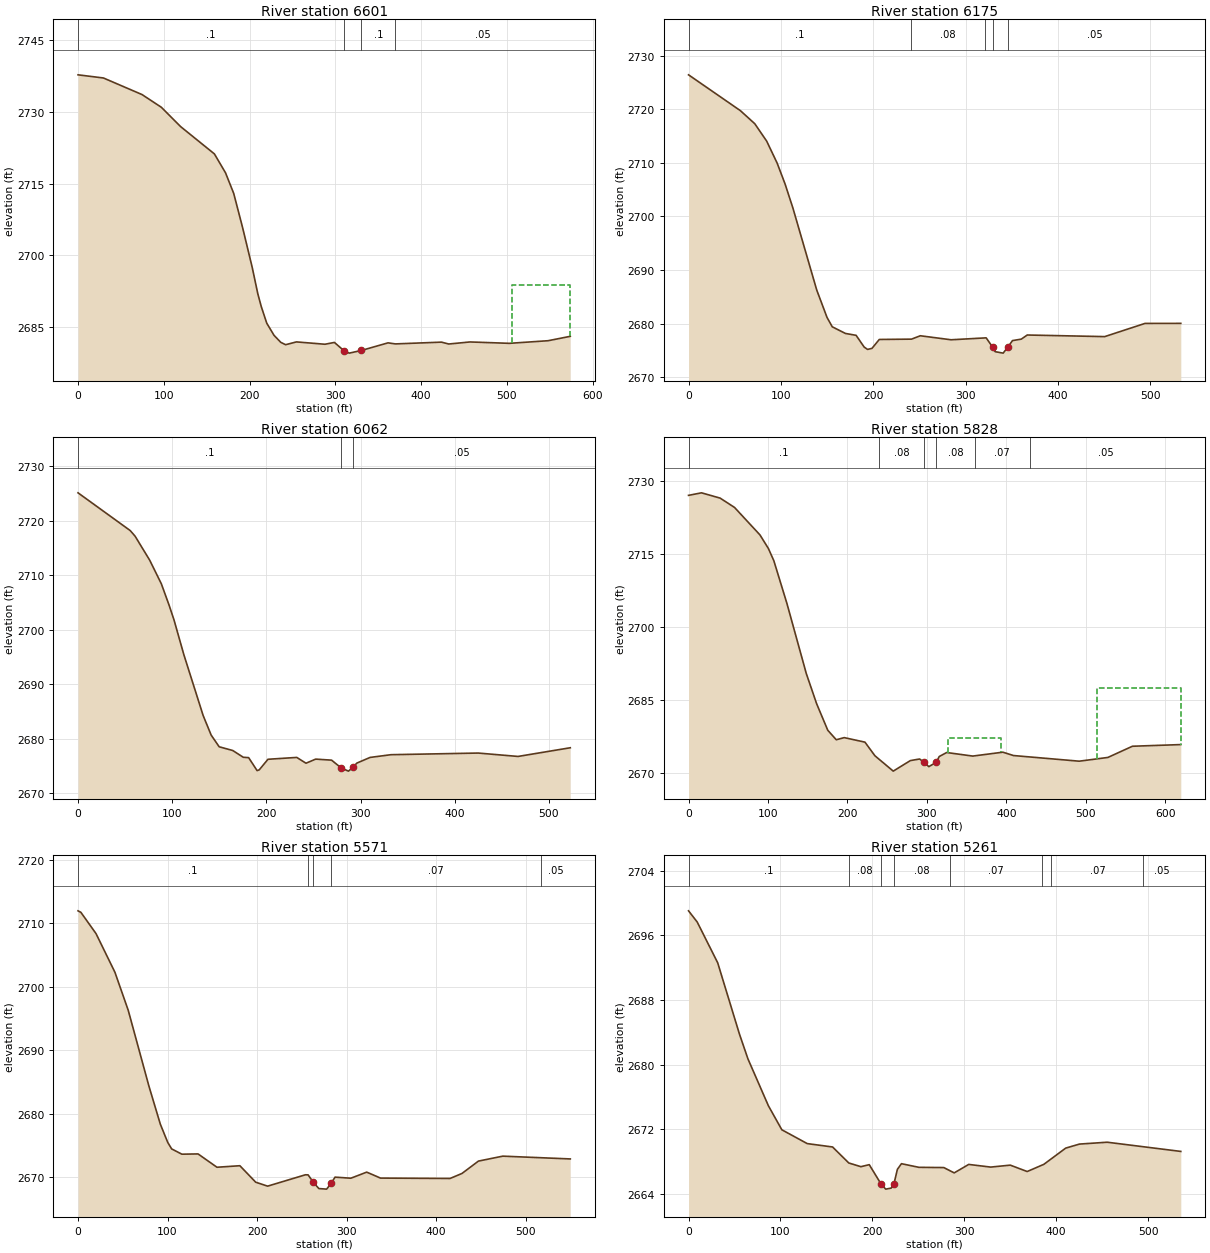
Type RM Length L Ch R = 1 ,6601    ,423.9,425.4,420.1
XS GIS Cut Line= 2
2312390.26649968536564.0887107852311986.95918486536972.327397311
#Sta/Elev= 30
       0  2737.8    29.6 2737.14    74.6 2733.67    97.1 2731.01   119.6 2726.96
     159 2721.24     172 2717.27   181.5 2712.97   191.8 2705.86   203.1 2697.46
   209.6 2691.96   213.6  2689.3     220 2685.81   228.5 2683.26   236.3  2681.8
     242 2681.29   254.6 2681.88   287.9 2681.39   298.9 2681.77   310.12680.026
   316.2 2679.53   330.4 2680.09   361.4 2681.68     370 2681.46   423.7 2681.83
   432.2 2681.44     457 2681.87   502.9 2681.58   548.1 2682.13   573.9 2683.05
#Mann= 4 ,-1,0
       0      .1       0   310.1    .045       0   330.4      .1       0
     370     .05       0
#XS Ineff= 2 , 0
                          506.31         2693.73
Permanent Ineff=
       F       F
Bank Sta=310.1,330.4
XS Rating Curve= 0 ,0
Exp/Cntr(USF)=0,0
Exp/Cntr=0.3,0.1

Type RM Length L Ch R = 1 ,6175    ,106,113.3,126.3
XS GIS Cut Line= 3
2312123.66716869536397.6830529392311991.55693955536505.611051677
2311795.85561593536810.470333967
#Sta/Elev= 30
       0  2726.4    56.1 2719.72    71.7 2717.28    84.6 2714.03    95.9 2709.94
   104.5 2706.04     113 2701.54   138.8 2686.24   149.9 2681.15   155.6 2679.39
   169.9 2678.15   181.4  2677.8   190.1 2675.62   193.8 2675.17   198.6 2675.37
   206.5 2677.03   241.4 2677.09   250.9 2677.72   284.2 2676.97   322.2 2677.33
   329.1 2675.62   331.9 2674.75   340.6 2674.48   345.9 2675.66   350.7 2676.82
   360.2 2677.09   366.7 2677.86   450.5 2677.56   494.1 2680.02   532.9 2680.03
#Mann= 5 ,-1,0
       0      .1       0  240.59     .08       0  320.59     .05       0
   329.1    .045       0   345.9     .05       0
Bank Sta=329.1,345.9
XS Rating Curve= 0 ,0
Exp/Cntr(USF)=0,0
Exp/Cntr=0.3,0.1

Type RM Length L Ch R = 1 ,6062    ,233.2,233.7,223.3
XS GIS Cut Line= 5
2312098.89180409536380.8368191492311881.21403443536560.421489207
2311853.17535807536560.2704275172311825.98655008536638.580670152
2311719.85672908536713.009375789
#Sta/Elev= 30
       0 2725.07    55.4 2718.16    60.6 2717.13    76.1 2712.74    88.5  2708.4
    96.9  2704.4     102 2701.75   112.4 2695.42   132.9 2684.27   141.4 2680.69
   149.9 2678.55   164.3 2677.87   175.5 2676.63   181.2 2676.56   190.2 2674.18
   192.5 2674.33   201.7 2676.26   232.3  2676.6   242.1 2675.54   252.4 2676.29
   269.3  2676.1   279.62674.654   287.2 2674.09     292 2674.79   296.1 2675.56
   310.2  2676.6   332.4  2677.1     425  2677.4   467.3 2676.78   522.8 2678.37
#Mann= 3 ,-1,0
       0      .1       0   279.6    .045       0     292     .05       0
Bank Sta=279.6,292
XS Rating Curve= 0 ,0
Exp/Cntr(USF)=0,0
Exp/Cntr=0.3,0.1

Type RM Length L Ch R = 1 ,5828    ,254.8,257.8,258.4
XS GIS Cut Line= 3
2312062.10661339536207.6237789522311580.12482026536499.647674409
2311574.36687097536555.514748722
#Sta/Elev= 30
       0 2726.99    16.3 2727.51    39.7 2726.43    57.9 2724.51    89.9 2718.87
   100.5 2716.09   107.4 2713.56   123.9 2704.77   148.2 2690.42   161.3 2684.18
   175.3 2678.75     186  2676.8     196 2677.24   222.1 2676.31   234.6 2673.52
   257.7 2670.36   279.2 2672.52   290.9 2672.85   296.3  2672.2   302.5 2671.28
   311.8 2672.17   315.6 2673.36     325 2674.18   357.8 2673.45   395.7 2674.25
   409.1 2673.56   491.8  2672.4   527.9 2673.17   558.8 2675.47   619.7 2675.81
#Mann= 6 ,-1,0
       0      .1       0     240     .08       0   296.3    .045       0
   311.8     .08       0     360     .07       0     430     .05       0
#XS Ineff= 2 ,-1
  326.74  393.022677.174  513.95   619.7 2687.41
Permanent Ineff=
       F       F
Bank Sta=296.3,311.8
XS Rating Curve= 0 ,0
Exp/Cntr(USF)=0,0
Exp/Cntr=0.3,0.1

Type RM Length L Ch R = 1 ,5571    ,302.2,309.8,304.7
XS GIS Cut Line= 4
2311895.20601348536073.0897149452311727.34302472536129.989343302
2311483.48464923536246.1123792512311455.90694143536344.846501448
#Sta/Elev= 30
       0 2711.96     3.2 2711.72    20.1 2708.37    41.2 2702.28    56.1 2696.27
    79.2 2684.32    91.9 2678.34   100.2 2675.45   104.6 2674.42     116 2673.59
   134.1 2673.63   155.2 2671.53   180.8 2671.77   198.5 2669.17   211.8 2668.55
     254 2670.34     257 2670.33     263 2669.13     269 2668.17   277.7 2668.08
282.79822668.994   287.1 2669.97   304.8  2669.8   322.5 2670.76   337.9 2669.82
   415.6 2669.76   428.9 2670.55   447.3  2672.5   474.5 2673.28   549.9 2672.84
#Mann= 5 ,-1,0
       0      .1       0  257.24     .07       0     263    .045       0
282.7982     .07       0  517.34     .05       0
Bank Sta=263,282.7982
XS Rating Curve= 0 ,0
Exp/Cntr(USF)=0,0
Exp/Cntr=0.3,0.1

Type RM Length L Ch R = 1 ,5261    ,140,140.6,139.3
XS GIS Cut Line= 3
2311808.30475407536016.2661363272311673.92642819535939.547564344
2311328.63708756536099.957691903
#Sta/Elev= 30
       0 2699.05     9.4 2697.67    31.7 2692.62    55.4 2683.78    64.6 2680.72
    86.9  2674.9   101.5 2671.93   129.1 2670.22   156.7  2669.8   174.3 2667.82
   187.5 2667.36   196.6 2667.61   209.6 2665.18   214.5 2664.58   220.5 2664.71
   223.5 2665.26   227.2 2667.03   231.6 2667.73   250.6 2667.28   277.7 2667.25
     289 2666.59   304.8 2667.64   328.7 2667.31     350 2667.55   368.4 2666.76
   386.5 2667.65   410.3 2669.66   425.3 2670.16   455.4 2670.39   535.5 2669.25
#Mann= 8 ,-1,0
       0      .1       0  174.74     .08       0   209.6    .045       0
   223.5     .08       0  284.74     .07       0  384.74     .05       0
  394.74     .07       0  494.74     .05       0
Bank Sta=209.6,223.5
XS Rating Curve= 0 ,0
Exp/Cntr(USF)=0,0
Exp/Cntr=0.3,0.1

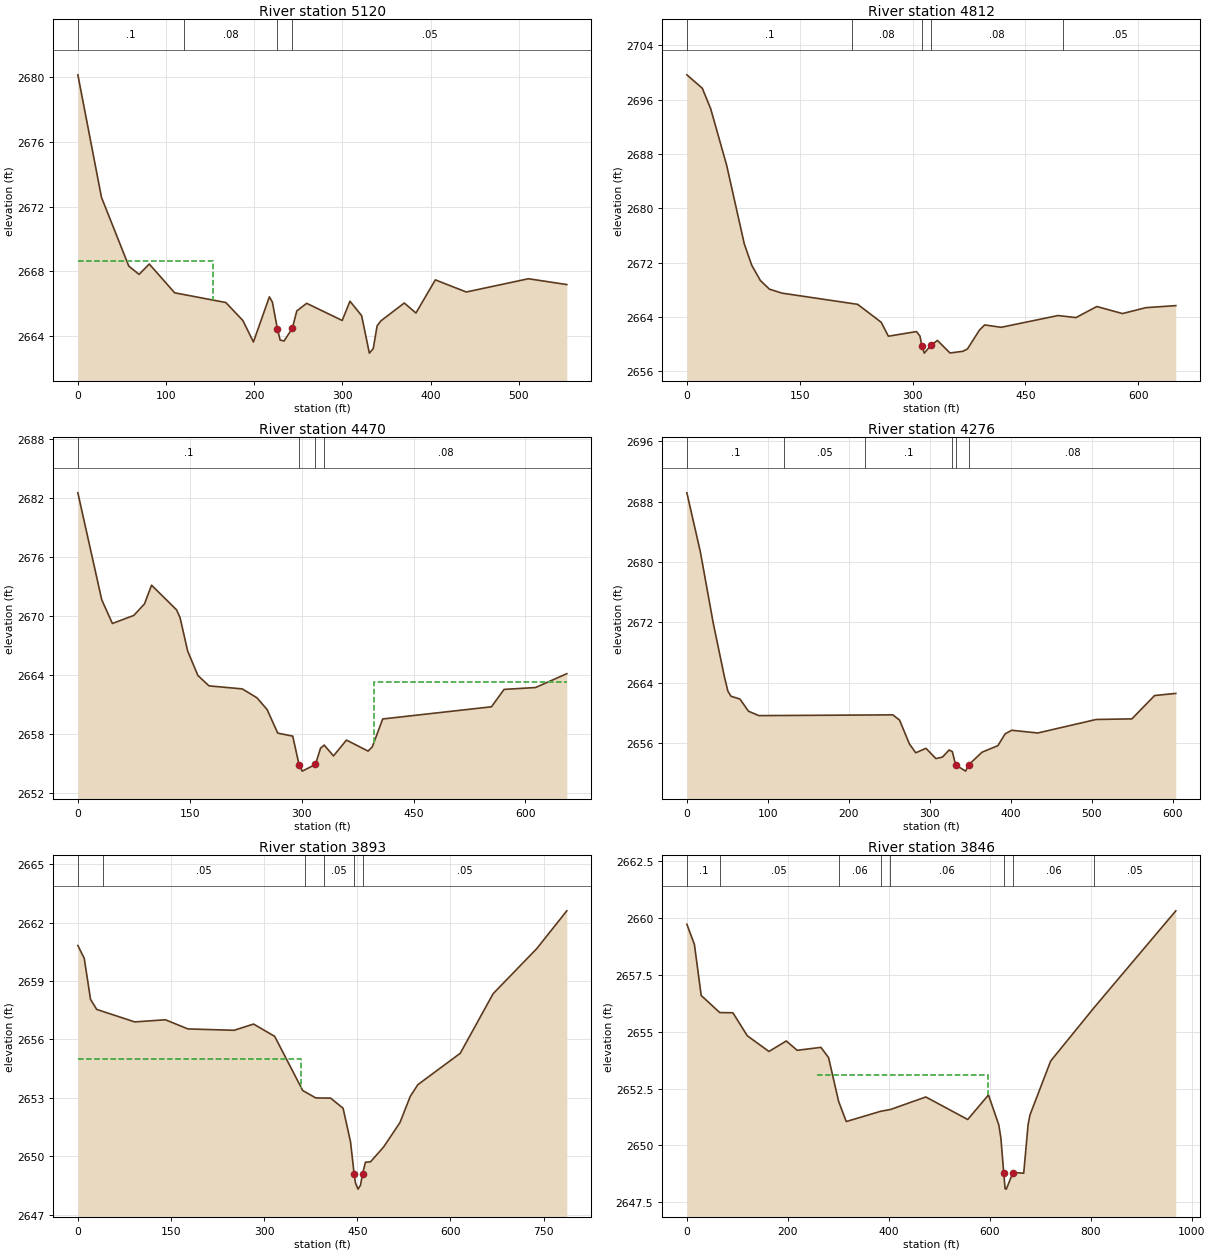
Type RM Length L Ch R = 1 ,5120    ,309.6,308,301.1
XS GIS Cut Line= 3
2311743.60024976535920.9678785922311628.63844417535811.812224799
2311268.59234143535976.624230383
#Sta/Elev= 30
       0 2680.15    26.8 2672.57    57.8 2668.32    69.4 2667.81      81 2668.45
   109.8 2666.67   167.8 2666.07   187.1 2664.96   199.1 2663.63   217.2 2666.42
   220.6  2666.1   226.3 2664.44   229.4 2663.75   233.8 2663.69   243.22664.467
   248.3 2665.55   259.5 2666.02   299.8 2664.96   308.6 2666.15   321.8 2665.26
   330.6 2662.94     335 2663.22   339.4 2664.63   343.8 2664.94   370.2 2666.04
   383.4 2665.42   405.4 2667.47   440.5 2666.72     511 2667.54   554.5 2667.18
#Mann= 4 ,-1,0
       0      .1       0     120     .08       0   226.3    .045       0
   243.2     .05       0
#XS Ineff= 2 , 0
          153.49 2668.63
Permanent Ineff=
       F       F
Bank Sta=226.3,243.2
XS Rating Curve= 0 ,0
Exp/Cntr(USF)=0,0
Exp/Cntr=0.3,0.1

Type RM Length L Ch R = 1 ,4812    ,343.6,341.8,339
XS GIS Cut Line= 2
2311710.87647486535397.0323455722311245.08387349 535850.39451042
#Sta/Elev= 30
       0 2699.65    20.5 2697.68    31.7 2694.65    52.9 2686.34    76.3 2674.79
    86.2 2671.64    97.7 2669.39   109.8 2668.11   126.4 2667.53     227 2665.88
   258.3 2663.25   267.9 2661.19   305.2 2661.87   309.9 2661.21  312.342659.796
   315.6  2658.7   324.5 2659.84   333.1 2660.57   349.8 2658.72   366.9 2658.97
     373 2659.31   388.9 2662.08   395.9 2662.85   417.8  2662.5   493.4 2664.23
   517.3 2663.93     545 2665.56   579.1 2664.52   610.2 2665.39     650 2665.69
#Mann= 5 ,-1,0
       0      .1       0     220     .08       0  312.34    .045       0
   324.5     .08       0     500     .05       0
Bank Sta=312.34,324.5
XS Rating Curve= 0 ,0
Exp/Cntr(USF)=0,0
Exp/Cntr=0.3,0.1

Type RM Length L Ch R = 1 ,4470    ,208.9,194.7,185.3
XS GIS Cut Line= 4
2311448.58644837535126.3790178492311317.42870782535327.579164889
2311210.59551475535478.5391116232311137.09211699535696.879921896
#Sta/Elev= 30
       0 2682.52      32 2671.64    46.3 2669.22      75 2670.04    89.3 2671.21
    98.8 2673.12   132.3 2670.61     137 2669.82   147.2 2666.42   160.9 2663.93
   175.8 2662.87   220.5 2662.56   240.2 2661.65   253.7 2660.46     268 2658.06
   288.1 2657.75   296.7 2654.79   300.9 2654.19   318.5 2654.87   325.4 2656.53
   330.3 2656.84   342.7 2655.74   360.1 2657.35   389.1 2656.23   394.7 2656.66
   408.7  2659.5   554.5 2660.74   571.4 2662.51   613.6  2662.7   655.5 2664.11
#Mann= 4 ,-1,0
       0      .1       0   296.7    .045       0   318.5      .1       0
  330.17     .08       0
#XS Ineff= 2 , 0
                          396.51         2663.28
Permanent Ineff=
       F       F
Bank Sta=296.7,318.5
XS Rating Curve= 0 ,0
Exp/Cntr(USF)=0,0
Exp/Cntr=0.3,0.1

Type RM Length L Ch R = 1 ,4276    ,379.6,383.1,384.2
XS GIS Cut Line= 4
2311162.08189084535045.5292131272311075.76462383 535288.62138734
2311103.92687251535431.259756626 2311114.3424205535631.305416695
#Sta/Elev= 30
       0 2689.16    16.6 2681.38    32.5 2671.95    46.3 2664.84    50.6 2662.91
    54.5 2662.22    65.5 2661.86      76 2660.25    88.9 2659.66   254.3 2659.76
   262.6 2659.07   274.8 2655.91   282.6 2654.74   295.2 2655.33   307.5 2653.97
   315.6 2654.17   323.8 2655.11   327.8 2654.89   331.9 2653.13   344.2 2652.31
   348.2 2653.17   364.5 2654.82     384 2655.68   393.1 2657.26   401.2 2657.72
   433.3 2657.36   505.4 2659.15   549.5 2659.23   577.5 2662.32   603.7  2662.6
#Mann= 6 ,-1,0
       0      .1       0     120     .05       0     220      .1       0
  327.96     .08       0   331.9    .045       0   348.2     .08       0
Bank Sta=331.9,348.2
XS Rating Curve= 0 ,0
Exp/Cntr(USF)=0,0
Exp/Cntr=0.3,0.1

Type RM Length L Ch R = 1 ,3893    ,50.1,46.8,48.2
BEGIN DESCRIPTION:
structure xs 4
END DESCRIPTION:
XS GIS Cut Line= 4
2310996.49920723535000.9652766822310774.75862126535292.196143372
2310786.35935674535467.5719360052310853.07284927535704.051244337
#Sta/Elev= 30
       0 2660.82    10.3 2660.16    20.4 2658.06    30.4 2657.54    91.7  2656.9
     141 2657.01   177.3 2656.54   251.6 2656.47     283 2656.79     317 2656.16
   362.2 2653.38   383.1    2653   407.1 2652.99   427.2 2652.47   439.2 2650.74
  445.012649.095   447.1 2648.64   451.2 2648.32   455.2 2648.52   458.5  2649.1
   463.2  2649.7   471.3 2649.72   492.4 2650.48   518.7 2651.73   535.4 2653.08
   547.6 2653.68   615.9 2655.29   668.9 2658.35   739.1 2660.66   787.5  2662.6
#Mann= 6 ,-1,0
       0      .1       0      40     .05       0  366.04     .06       0
  396.04     .05       0  445.01    .045       0   458.5     .05       0
#XS Ineff= 2 , 0
             360    2655
Permanent Ineff=
       F       F
Bank Sta=445.01,458.5
XS Rating Curve= 0 ,0
Exp/Cntr(USF)=0,0
Exp/Cntr=0.5,0.3

Type RM Length L Ch R = 1 ,3846    ,66.7,66.2,65
BEGIN DESCRIPTION:
structure xs 3; 11.8 ft between structure and xs
END DESCRIPTION:
XS GIS Cut Line= 6
2310916.08109905534905.3518539082310658.46254989535100.040681136
2310722.32350052535333.3017439622310760.88796076 535497.90614742
2310786.28854757535601.5119027842310825.61962377535723.438239029
#Sta/Elev= 30
       0 2659.72    14.9 2658.84    28.4 2656.59    65.1 2655.84    91.2 2655.83
   119.7 2654.82   162.6 2654.13   196.9 2654.59   218.6 2654.18   265.6 2654.31
   280.7 2653.86   300.7 2651.93   315.8 2651.05   383.8  2651.5   403.4 2651.58
   473.4 2652.13   556.4 2651.14   597.5 2652.22     618  2650.9   622.1 2650.32
  627.842648.769   630.4  2648.1   632.8 2648.08   646.1 2648.81   667.3 2648.78
     676 2650.92   679.7 2651.34   720.7 2653.71   807.2 2656.07   968.6 2660.31
#Mann= 8 ,-1,0
       0      .1       0    65.1     .05       0   300.7     .06       0
   383.8     .05       0   403.4     .06       0  627.84    .045       0
   646.1     .06       0   807.2     .05       0
#XS Ineff= 3 ,-1
  257.46  597.18 2653.09  597.18     615  2648.6     658   968.6  2648.1
Permanent Ineff=
       F       F       F
Bank Sta=627.84,646.1
XS Rating Curve= 0 ,0
Exp/Cntr(USF)=0,0
Exp/Cntr=0.5,0.3