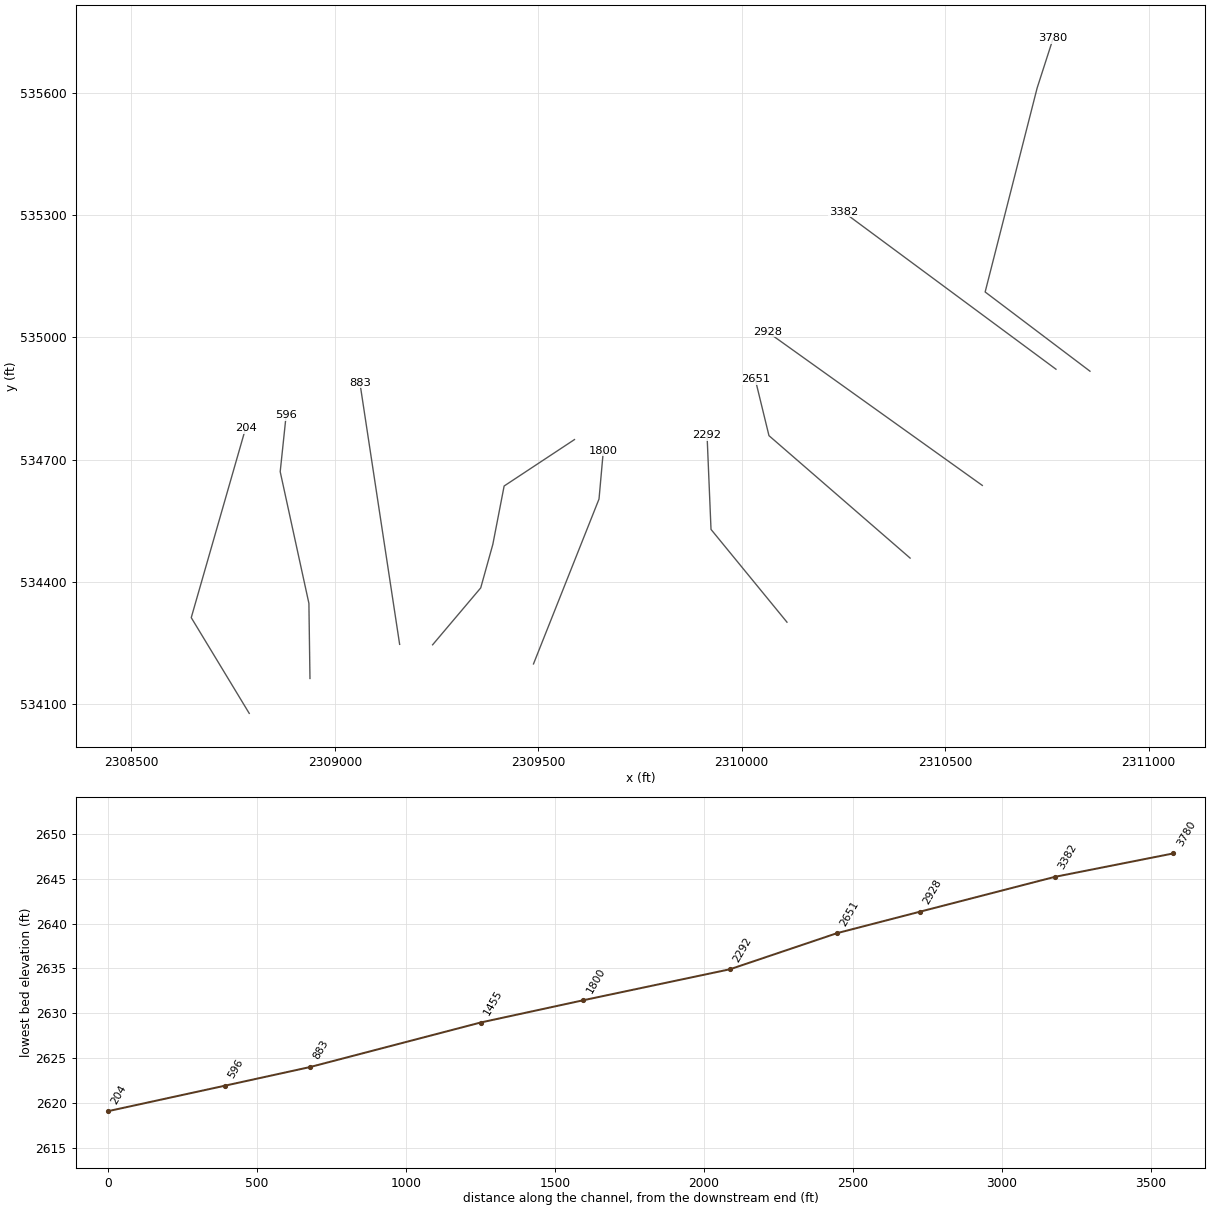
HEC-RAS study BFFLRN.prj: BFFLRN

--- BFFLRN.g01 (geometry) --- (continued)

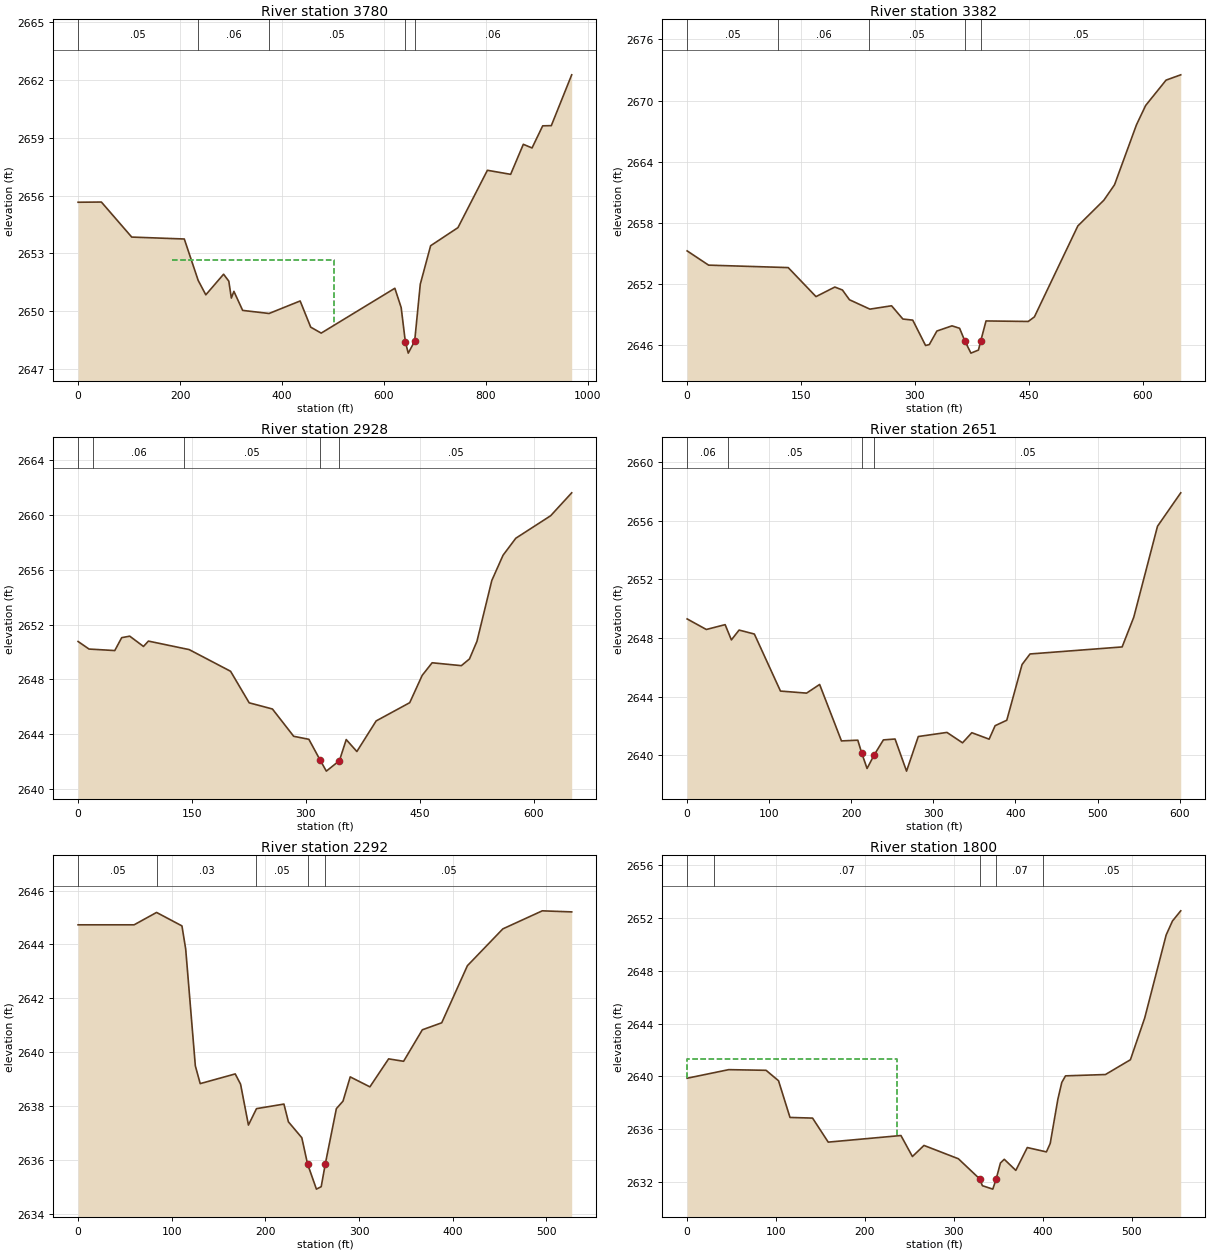
Type RM Length L Ch R = 1 ,3780    ,384.1,397.7,415.8
BEGIN DESCRIPTION:
structure xs 2; 15.2 ft between structure and xs
END DESCRIPTION:
XS GIS Cut Line= 4
2310856.10120783 534917.151176772310598.48265867535111.840003998
2310726.30865635535613.3112256472310765.63973256535735.237561891
#Sta/Elev= 30
       0 2655.65    45.7 2655.66   105.2 2653.84   208.4 2653.74   235.6 2651.59
   250.6 2650.84   285.5 2651.91   295.7 2651.55   300.7 2650.67   305.7 2651.02
   322.9 2650.03   374.7 2649.87   435.7 2650.52   456.4 2649.16     477 2648.85
   621.5 2651.18   633.9 2650.18   642.1  2648.4   647.8 2647.81   660.4 2648.43
   671.4 2651.39   691.7 2653.39   745.3 2654.33   803.1 2657.31   848.7  2657.1
   873.6 2658.66   890.7 2658.47   911.6 2659.62   928.5 2659.63   968.5 2662.27
#Mann= 5 ,-1,0
       0     .05       0   235.6     .06       0   374.7     .05       0
   642.1    .045       0   660.4     .06       0
#XS Ineff= 3 ,-1
  184.69  502.75 2652.67  502.75     638  2648.6     665   968.5  2648.1
Permanent Ineff=
       F       F       F
Bank Sta=642.1,660.4
XS Rating Curve= 0 ,0
Exp/Cntr(USF)=0,0
Exp/Cntr=0.5,0.3

Type RM Length L Ch R = 1 ,3382    ,446.8,453.9,447.6
BEGIN DESCRIPTION:
structure xs 1
END DESCRIPTION:
XS GIS Cut Line= 2
 2310772.5685297534922.0167505222310250.05009126535308.636048393
#Sta/Elev= 30
       0 2655.24    28.3 2653.84   133.1  2653.6   169.7 2650.75   194.5 2651.69
   204.5  2651.4   213.8 2650.44   240.7 2649.52   269.2 2649.85   284.1 2648.55
   297.1 2648.44     314 2645.95   318.9 2646.04   328.9 2647.37   348.8 2647.88
   358.8 2647.64   365.7  2646.4   373.7  2645.2   383.6  2645.5   386.7 2646.41
   393.6 2648.36   449.2 2648.31   457.3 2648.76   514.5 2657.69   548.8 2660.22
   562.8 2661.73   591.7 2667.62   603.8 2669.52   630.7 2672.01     650 2672.53
#Mann= 5 ,-1,0
       0     .05       0     120     .06       0     240     .05       0
   365.7    .045       0   386.7     .05       0
Bank Sta=365.7,386.7
XS Rating Curve= 0 ,0
Exp/Cntr(USF)=0,0
Exp/Cntr=0.3,0.1

Type RM Length L Ch R = 1 ,2928    ,256.6,277.1,227.5
XS GIS Cut Line= 2
2310591.48495308 534636.415857382310062.65340255535014.353935883
#Sta/Elev= 30
       0 2650.76    14.4 2650.21    48.3  2650.1    57.4 2651.04      68 2651.15
    86.1  2650.4    92.6 2650.79   146.3 2650.17   200.8 2648.59   225.3 2646.29
   255.9 2645.84   283.9 2643.85   303.9 2643.63   318.7 2642.12   326.9 2641.31
   344.1 2642.07   353.1 2643.61   367.1 2642.74   392.5 2644.97   436.7  2646.3
   453.1 2648.29   466.2 2649.21   504.7    2649   515.4 2649.49   525.2 2650.77
   544.8 2655.21   559.6 2657.05   576.4 2658.29   622.3 2659.93     650  2661.6
#Mann= 5 ,-1,0
       0     .05       0      20     .06       0     140     .05       0
   318.7    .045       0   344.1     .05       0
Bank Sta=318.7,344.1
XS Rating Curve= 0 ,0
Exp/Cntr(USF)=0,0
Exp/Cntr=0.3,0.1

Type RM Length L Ch R = 1 ,2651    ,317.1,359.3,292.4
XS GIS Cut Line= 3
2310414.07752812534457.8303690032310067.17743596534758.713101993
2310033.54936581534896.765179482
#Sta/Elev= 30
       0 2649.31    23.4 2648.59    46.3 2648.92    53.9 2647.88    63.3 2648.55
    81.9 2648.28   113.7 2644.39   145.5 2644.25   161.4 2644.84     188 2640.99
   207.9 2641.04   212.7 2640.16   219.2 2639.11   227.7 2640.02   239.1 2641.06
   253.3 2641.12   267.3 2638.93   281.6 2641.29   316.5 2641.57   335.5 2640.86
   346.8 2641.55   367.9 2641.11   375.2 2642.03   389.4  2642.4     408  2646.2
   417.7 2646.92   529.9  2647.4   544.1 2649.43     573 2655.63   601.3 2657.91
#Mann= 4 ,-1,0
       0     .06       0      50     .05       0   212.7    .045       0
   227.7     .05       0
Bank Sta=212.7,227.7
XS Rating Curve= 0 ,0
Exp/Cntr(USF)=0,0
Exp/Cntr=0.3,0.1

Type RM Length L Ch R = 1 ,2292    ,455.9,492,366.8
XS GIS Cut Line= 3
 2310111.4248967534300.3094087912309924.73721912534528.291397059
2309914.96617104534760.483000423
#Sta/Elev= 30
       0 2644.73    59.8 2644.73    83.8 2645.19   110.9 2644.69   114.9 2643.83
   125.2 2639.49   130.4 2638.83   167.8 2639.19   173.5 2638.81   181.9 2637.29
   190.5  2637.9   219.8 2638.07   224.6 2637.41   238.9 2636.82     245 2635.85
   254.5 2634.91   259.6    2635     264 2635.85   275.8  2637.9   282.9 2638.18
   290.6 2639.08   311.6 2638.71   331.6 2639.75   347.6 2639.66   367.6 2640.83
   388.3 2641.09   415.7 2643.21   453.6 2644.58   495.7 2645.25   527.1 2645.21
#Mann= 5 ,-1,0
       0     .05       0    83.8     .03       0   190.5     .05       0
     245    .045       0     264     .05       0
Bank Sta=245,264
XS Rating Curve= 0 ,0
Exp/Cntr(USF)=0,0
Exp/Cntr=0.3,0.1

Type RM Length L Ch R = 1 ,1800    ,335.1,344.6,340.4
XS GIS Cut Line= 3
2309488.42064957534197.6552998892309649.48140664 534602.96204021
2309660.10079721534721.545234977
#Sta/Elev= 30
       0 2639.86    46.8 2640.51    88.8 2640.46   102.8 2639.67   115.7 2636.89
   141.1 2636.84   158.7 2635.02   240.5 2635.52   253.4 2633.93   266.4 2634.77
   305.1 2633.76     329 2632.24   332.1 2631.72   343.8 2631.46   347.5  2632.2
   352.4 2633.44   356.7 2633.72   369.7 2632.88   382.6 2634.61   404.1 2634.28
   408.4 2634.92     417 2638.27   421.4 2639.54   425.6 2640.04   470.5 2640.14
   498.6 2641.26   514.7 2644.43   538.8 2650.71   545.9 2651.77   555.2 2652.54
#Mann= 5 ,-1,0
       0     .05       0      30     .07       0     329    .045       0
   347.5     .07       0     400     .05       0
#XS Ineff= 2 , 0
          236.21 2641.34
Permanent Ineff=
       F       F
Bank Sta=329,347.5
XS Rating Curve= 0 ,0
Exp/Cntr(USF)=0,0
Exp/Cntr=0.3,0.1

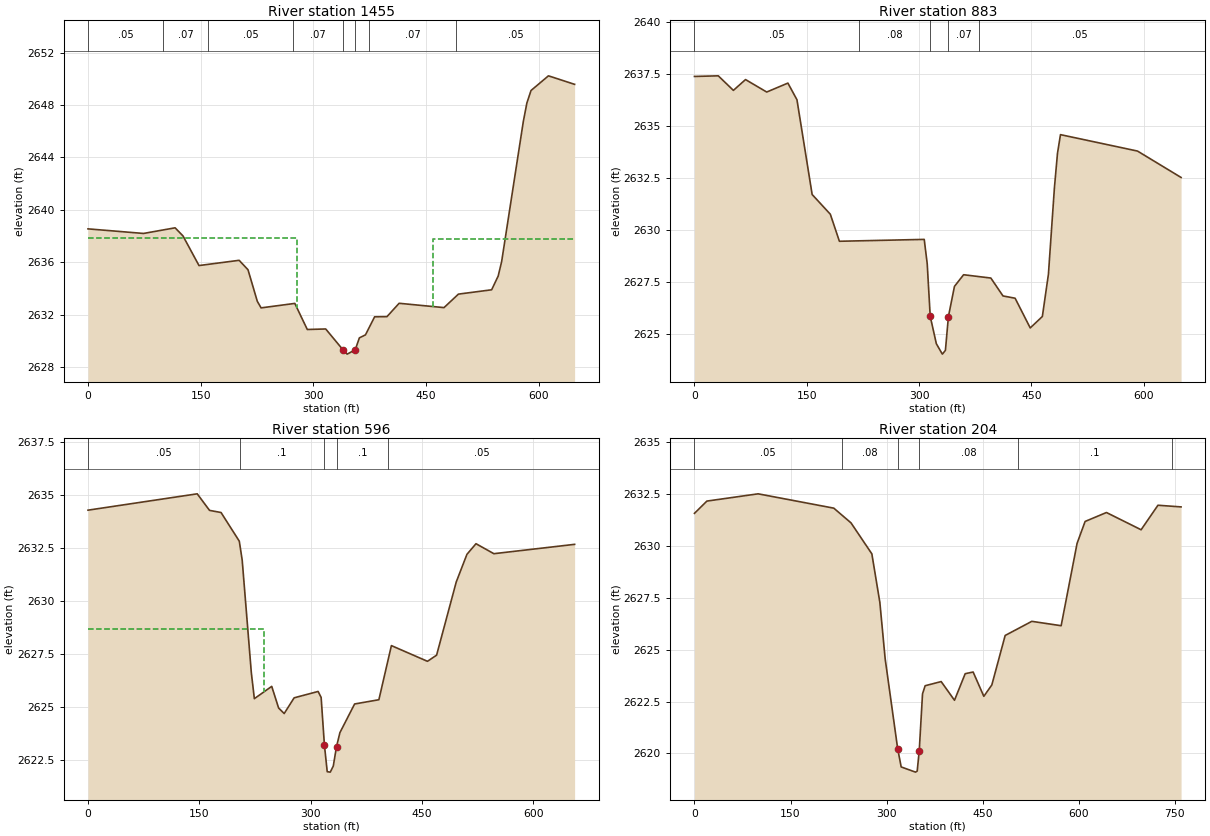
Type RM Length L Ch R = 1 ,1455    ,558.9,572.6,569.1
XS GIS Cut Line= 5
2309240.47975361534244.6728451152309358.70045863534384.508464557
2309388.48343906534491.4979907992309416.28245267534634.982351807
2309589.14974419 534749.09389748
#Sta/Elev= 30
       0 2638.54    73.9 2638.19   115.9 2638.62   126.4    2638   147.7 2635.74
   201.1 2636.14   212.9 2635.42   225.3 2633.01   230.3 2632.51   275.2 2632.85
   291.8 2630.86   316.3  2630.9   339.7 2629.28   344.8 2628.98   355.6 2629.31
   361.1 2630.22   369.2 2630.45   381.4 2631.83   397.8 2631.84     414 2632.86
   473.7 2632.53   492.9 2633.56   537.1 2633.89   545.8 2634.94   550.4 2636.04
   579.2 2646.72     584 2648.15   589.5  2649.1   612.7 2650.22   647.5 2649.57
#Mann= 8 ,-1,0
       0     .05       0     100     .07       0     160     .05       0
  273.11     .07       0   339.7    .045       0   355.6     .05       0
  374.17     .07       0  490.32     .05       0
#XS Ineff= 2 , 0
          277.91 2637.88   459.3         2637.73
Permanent Ineff=
       F       F
Bank Sta=339.7,355.6
XS Rating Curve= 0 ,0
Exp/Cntr(USF)=0,0
Exp/Cntr=0.3,0.1

Type RM Length L Ch R = 1 ,883     ,282.1,286.2,283.9
XS GIS Cut Line= 2
2309159.43941667534245.789206541 2309061.7725317534888.409762995
#Sta/Elev= 30
       0 2637.38    31.8 2637.41      52 2636.71    68.2 2637.23    96.5 2636.63
   124.8 2637.06   136.9 2636.26   157.2  2631.7   181.5 2630.75   193.6 2629.45
   306.9 2629.54   310.9 2628.37   314.9 2625.84   323.1 2624.52   331.1 2624.02
   335.2  2624.2   339.2 2625.82   347.3 2627.28   359.5 2627.84   395.9 2627.68
   412.1 2626.82   428.3 2626.71   448.5 2625.28   464.7 2625.83   472.8 2627.86
   480.8 2632.02   484.9 2633.68   488.9 2634.58   591.8 2633.79     650 2632.52
#Mann= 5 ,-1,0
       0     .05       0     220     .08       0   314.9    .045       0
   339.2     .07       0     380     .05       0
Bank Sta=314.9,339.2
XS Rating Curve= 0 ,0
Exp/Cntr(USF)=0,0
Exp/Cntr=0.3,0.1

Type RM Length L Ch R = 1 ,596     ,392.5,392.5,392.5
XS GIS Cut Line= 4
2308939.06405703534161.9454324512308936.43186896534346.576235138
2308865.88712462534670.1414625092308880.55622658534809.306872279
#Sta/Elev= 30
       0 2634.28   147.2 2635.05   163.8 2634.27   179.3 2634.17   203.9 2632.82
   207.8 2631.93   220.1 2626.63   224.2  2625.4   247.6 2625.98   256.9 2624.96
   264.4  2624.7   277.8 2625.44   310.1 2625.74   314.2 2625.46   318.6 2623.22
   322.4 2621.96   326.5 2621.94   330.6 2622.23   334.9 2623.14   339.5  2623.8
   359.3 2625.15     392 2625.35   408.9  2627.9   457.5 2627.16   469.8 2627.45
   496.3  2630.9   510.7  2632.2   522.9  2632.7     547 2632.23   655.8 2632.67
#Mann= 5 ,-1,0
       0     .05       0  204.65      .1       0   318.6    .045       0
   334.9      .1       0  404.65     .05       0
#XS Ineff= 2 , 0
          237.21 2628.66
Permanent Ineff=
       F       F
Bank Sta=318.6,334.9
XS Rating Curve= 0 ,0
Exp/Cntr(USF)=0,0
Exp/Cntr=0.3,0.1

Type RM Length L Ch R = 1 ,204     ,204,204,204
XS GIS Cut Line= 3
2308789.78729595534076.1409886022308647.26472789534311.437607802
 2308780.9413337534777.175193088
#Sta/Elev= 30
       0 2631.56    19.4 2632.15    99.4  2632.5   217.5 2631.81   244.4  2631.1
   276.9 2629.61   289.4 2627.27   297.7 2624.55   317.2 2620.23   322.7 2619.35
   345.1  2619.1   347.7 2619.15   350.9 2620.14     356 2622.87   360.1 2623.26
   385.1 2623.46   405.9 2622.56   422.6 2623.84     435 2623.92   451.7 2622.75
   464.2  2623.3     485 2625.68   526.6 2626.36   572.4 2626.15   597.3 2630.12
   609.8 2631.17   643.1  2631.6   697.2 2630.77   723.5 2631.95   759.6 2631.87
#Mann= 6 ,-1,0
       0     .05       0     230     .08       0   317.2    .045       0
   350.9     .08       0  505.09      .1       0  745.09     .05       0
Bank Sta=317.2,350.9
XS Rating Curve= 0 ,0
Exp/Cntr(USF)=0,0
Exp/Cntr=0.3,0.1
LCMann Table=0

Chan Stop Cuts=-1
Use User Specified Reach Order=0
Composite Channel Slope=5